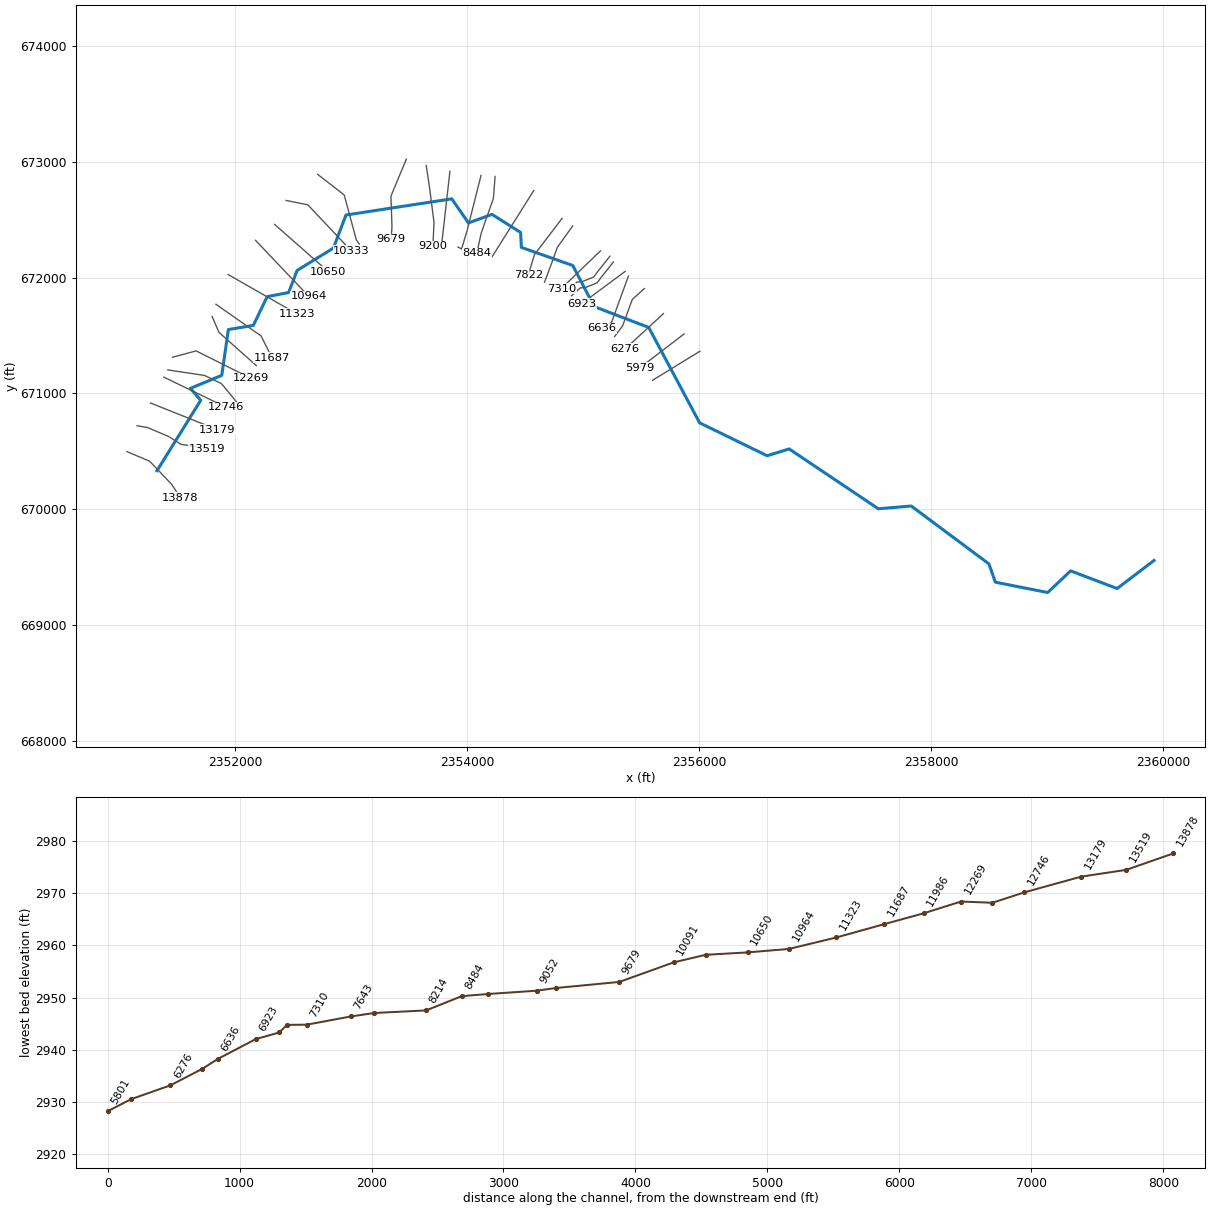
--- BEAVERDMRN.prj (project) ---

Proj Title=BEAVERDMRN
Current Plan=p01
Default Exp/Contr=0,0
English Units
Geom File=g01
Flow File=f01
Plan File=p01
BEGIN DESCRIPTION:
----------MODEL BY WOOD PLC 2022----------
AFH study
Randolph County, WV
HEC-RAS Version: RAS 6.2
Vertical Datum: NAVD88
Projection: NAD 1983 StatePlane West Virginia S FIPS 4702 (US Feet)
Terrain: 1-meter LIDAR (FEMA Region III 3DEP collected 2016-2018)
Land Use: 2019 NLCD
Hydrologic Method:
WV SIR2010-5033 regression equations
Additional Model Notes:
None
END DESCRIPTION:
DSS Export Rating Curves= 0
DSS Export Rating Curve Sorted= 0
DSS Export Volume Flow Curves= 0
DXF OffsetX= 0
DXF OffsetY= 0
DXF ScaleX= 0
DXF ScaleY= 0

--- BEAVERDMRN.p01 (plan) ---

Plan Title=Floodplain
Program Version=6.20
Short Identifier=Floodplain
Geom File=g01
Flow File=f01
Subcritical Flow
K Sum by GR= 0
Std Step Tol= 0.01
Critical Tol= 0.01
Num of Std Step Trials= 20
Max Error Tol= 0.3
Flow Tol Ratio= 0.001
Split Flow NTrial= 30
Split Flow Tol= 0.02
Split Flow Ratio= 0.02
Log Output Level= 0
Friction Slope Method= 1
Unsteady Friction Slope Method= 2
Unsteady Bridges Friction Slope Method= 1
Parabolic Critical Depth
Global Vel Dist= 0 , 0 , 0
Global Log Level= 0
CheckData=True
Encroach Param=-1 ,0,0, 0
Mapping Interval=1HOUR
Computation Time Step Use Courant=        0
Computation Time Step Use Time Series=    0
Computation Time Step Count To Double=0
Computation Time Step Max Doubling=0
Computation Time Step Max Halving=0
Computation Time Step Residence Courant=0
Run HTab= 0
Run UNet= 0
Run Sediment= 0
Run PostProcess= 0
Run WQNet= 0
Run RASMapper=-1
UNET Theta= 0
UNET Theta Warmup= 0
UNET ZTol= 0
UNET ZSATol= 0
UNET MxIter= 0
UNET Max Iter WO Improvement= 0
UNET MaxInSteps= 0
UNET DtIC= 0
UNET DtMin= 0
UNET MaxCRTS= 0
UNET WFStab= 0
UNET SFStab= 0
UNET WFX= 1
UNET SFX= 1
UNET Gravity=32.174
UNET 1D Methodology=Finite Difference
UNET DSS MLevel= 1
UNET Pardiso=0
UNET DZMax Abort= 0
UNET Use Existing IB Tables= 0
UNET Froude Reduction=False
UNET Froude Limit= 0
UNET Froude Power= 0
UNET D1 Cores= 0
UNET WindReference=Eulerian
UNET WindDragFormulation=Hsu (1988)
UNET D2 Coriolis=0
UNET D2 Cores= 0
UNET D2 Theta= 1
UNET D2 Theta Warmup= 1
UNET D2 Z Tol= 0.01
UNET D2 Volume Tol= 0.01
UNET D2 Max Iterations= 20
UNET D2 Equation= 0
UNET D2 RampUpFraction=0.1
UNET D2 TimeSlices= 1
UNET D2 Turbulence Formulation=Non-Conservative (original)
UNET D2 Eddy Viscosity=0.3
UNET D2 Transverse Eddy Viscosity=0.1
UNET D2 Smagorinsky Mixing=0
UNET D2 BCVolumeCheck=0
UNET D2 Cores=0
UNET D2 SolverType=PARDISO (Direct)
UNET D2 Minimum Iterations= 2147483647
UNET D2 Maximum Iterations= 2147483647
UNET D2 Restart Number= 10
UNET D2 Relaxation Coeff=1.3
UNET D2 SOR Precondition Iterations= 10
UNET D2 ILUT Maximum Fill= 8
UNET D2 ILUT Tolerance=1E-08
UNET D1D2 MaxIter= 0
UNET D1D2 ZTol=0.01
UNET D1D2 QTol=0.1
UNET D1D2 MinQTol=1
Write IC File= 0
Write IC File at Fixed DateTime=0
Write IC File at Sim End=0
Echo Input=False
Echo Parameters=False
Echo Output=False
Write Detailed= 0
HDF Write Warmup=0
HDF Write Time Slices=0
HDF Flush=0
HDF Compression= 1
HDF Chunk Size= 1
HDF Spatial Parts= 1
HDF Use Max Rows=0
HDF Fixed Rows= 1
Calibration Method= 0
Calibration Iterations= 20
Calibration Max Change=0.05
Calibration Tolerance=0.2
Calibration Maximum=1.5
Calibration Minimum=0.5
Calibration Optimization Method= 1
WQ AD Non Conservative
WQ ULTIMATE=-1
WQ Max Comp Step=1HOUR
WQ Output Interval=15MIN
WQ Output Selected Increments= 0
WQ Output face flow=0
WQ Output face velocity=0
WQ Output face area=0
WQ Output face dispersion=0
WQ Output cell volume=0
WQ Output cell surface area=0
WQ Output cell continuity=0
WQ Output cumulative cell continuity=0
WQ Output face conc=0
WQ Output face dconc_dx=0
WQ Output face courant=0
WQ Output face peclet=0
WQ Output face adv mass=0
WQ Output face disp mass=0
WQ Output cell mass=0
WQ Output cell source sink temp=0
WQ Output nsm pathways=0
WQ Output nsm derived pathways=0
WQ Create Restart=0
WQ Fixed Restart=0
WQ System Summary=0
WQ Write To DSS=0
Sorting and Armoring Iterations= 10
XS Update Threshold= 0.02
Bed Roughness Predictor= 0
Hydraulics Update Threshold= 0.02
Energy Slope Method= 1
Volume Change Method= 1
Sediment Retention Method= 0
Sediment TS Multiplier= 1
Warm Up Method= 0
XS Weighting Method= 0
Number of US Weighted Cross Sections= 1
Number of DS Weighted Cross Sections= 1
Upstream XS Weight=0
Main XS Weight=1
Downstream XS Weight=0
Number of DS XS's Weighted with US Boundary= 1
Upstream Boundary Weight= 1
Weight of XSs Associated with US Boundary= 0
Number of US XS's Weighted with DS Boundary= 1
Downstream Boundary Weight= 0.5
Weight of XSs Associated with DS Boundary= 0.5
Percentile Method= 0
Sediment Output Level= 3
Mass or Volume Output= 0
Output Increment Type= 1
Profile and TS Output Increment= 1
Transport Output Increment 1
XS Output Flag= 0
XS Output Increment= 10
Read HDF5 Sediment Hotstart= 0
Sediment Hotstart Type= 0
Write Gradation File= 0
Read Gradation Hotstart= 0
Write HDF5 File= 1
Write Binary Output= 1
Write DSS Sediment File= 0
DSS Sediment Output Type= 1
SV Curve= 0
Specific Gage Flag= 0
Subcell Erosion Methods= 0
Subcell Deposition Methods= 0
Advection Scheme= 1
Matrix Solver= 0
Implicit Weighting Factor= 1
Maximum Outer Loop Convergence Iterations= 5
Convergence Maximum Absolute= 0.001
Convergence RMSE= 0.0001
Grain Fractions Max Abs Error= 0.001
Max Subgrid Regions= 1
Max Subgrid Length Scale= 3.402823E+38
Initial Layer Thickness= 3.402823E+38
Min Layer Thickness= 3.402823E+38
Max Layer Thickness= 3.402823E+38
Number of Layers= 5

--- BEAVERDMRN.f01 (steady flow) ---

Flow Title=Flow
Program Version=6.20
Number of Profiles= 1
Profile Names=P100yr
River Rch & RM=BEAVERDMRN,Main,13878
     374
River Rch & RM=BEAVERDMRN,Main,11687
     419
River Rch & RM=BEAVERDMRN,Main,9679
     518
River Rch & RM=BEAVERDMRN,Main,7160
     640
River Rch & RM=BEAVERDMRN,Main,4694
     721
Boundary for River Rch & Prof#=BEAVERDMRN,Main            , 1
Up Type= 0
Dn Type= 3
Dn Slope=0.01731
DSS Import GetInterval= 0
DSS Import GetPeak= 0
DSS Import FillOption= 0

--- BEAVERDMRN.g01 (geometry) ---

Geom Title=Geometry
Program Version=6.20

River Reach=BEAVERDMRN      ,Main
Reach XY= 30
2351323.36122209670333.0964657052351700.90049547670941.497441088
 2351611.5713716671044.0153927492351882.03605917671156.380255994
     2351939.065      671551.2552352154.16958042671587.056866828
     2352273.412        671835.1     2352458.873      671870.876
     2352531.987      672061.2712352845.11091263672254.691211799
2352952.76836181672539.3179699082353864.95384528672679.029661633
2354008.87479212672471.389567551 2354211.8440917672545.144623106
2354458.65653333672389.006665081 2354464.9690917672260.077246212
2354908.72033764672103.7195581242355092.37345559671749.695926284
     2355563.178      671569.4522356002.04822238670746.360154514
 2356583.8926695670462.804207305     2356773.989      670521.303
2357542.73117052670005.176076684     2357826.397      670029.067
2358496.20319855669529.573135733 2358551.3160101669372.030261364
2359002.66028015669282.7361833962359200.56369214669469.394277538
2359601.49381749669317.202705084     2359919.943      669559.383

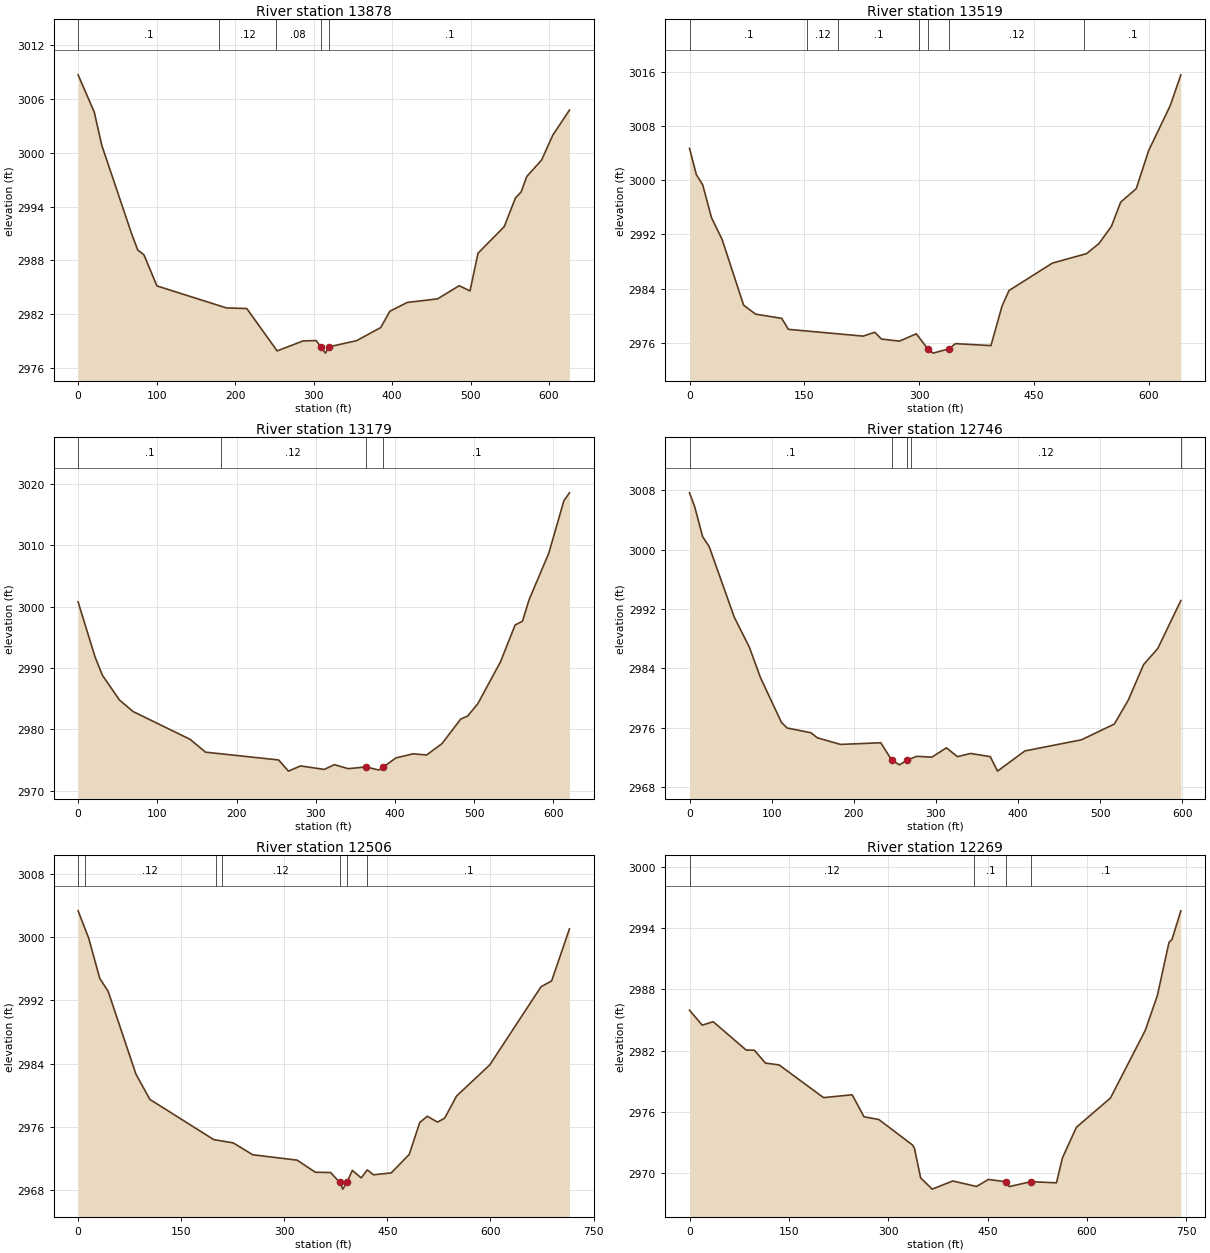
Type RM Length L Ch R = 1 ,13878   ,349.3,358.8,355.9
XS GIS Cut Line= 4
2351065.18129673 670497.740148292351260.13861667670415.600649346
2351449.93314484 670216.273062692351525.56437815 670099.42067843
#Sta/Elev= 30
       0 3008.72    20.6 3004.55    30.2 3000.84    68.4 2990.91      76 2989.15
    83.9 2988.61   100.4 2985.14     189 2982.68   214.9 2982.61   253.6 2977.88
   286.9    2979   303.3 2979.03   309.22978.347   315.1 2977.63   319.8 2978.34
   354.8 2979.02   385.6 2980.49   397.2 2982.31   419.3 2983.29   457.9 2983.69
   485.5 2985.16   499.3 2984.58   509.5 2988.79   542.9 2991.76   557.2 2994.97
   564.5 2995.64   571.6 2997.36   590.5  2999.2   604.8 3001.98     626 3004.78
#Mann= 5 ,-1,0
       0      .1       0     180     .12       0  251.55     .08       0
   309.2    .045       0   319.8      .1       0
Bank Sta=309.2,319.8
XS Rating Curve= 0 ,0
Exp/Cntr(USF)=0,0
Exp/Cntr=0.3,0.1

Type RM Length L Ch R = 1 ,13519   ,313.3,339.9,333
XS GIS Cut Line= 5
2351151.27503041670721.7388431192351243.67242473670705.058970838
 2351423.9338944  670628.79450292351530.53082118670561.196451773
2351753.70605907670524.358414051
#Sta/Elev= 30
       0 3004.68       9 3000.79    17.2 2999.31    28.8 2994.44    42.6 2991.24
    70.7 2981.55    86.3 2980.22   120.5  2979.6   129.2 2977.98     227 2976.98
   242.1 2977.55   250.8 2976.55   274.3 2976.24   296.4 2977.32   311.3  2975.1
   318.3 2974.47   338.8  2975.1   347.5 2975.87   393.9 2975.58   408.3 2981.39
   417.5 2983.71   474.3 2987.76   518.9 2989.15   535.1 2990.65   551.3 2993.18
   563.4 2996.75   583.7 2998.73   599.9 3004.34   628.3 3011.03     642 3015.53
#Mann= 7 ,-1,0
       0      .1       0  153.89     .12       0  193.89      .1       0
  299.62     .12       0   311.3    .045       0   338.8     .12       0
  515.85      .1       0
Bank Sta=311.3,338.8
XS Rating Curve= 0 ,0
Exp/Cntr(USF)=0,0
Exp/Cntr=0.3,0.1

Type RM Length L Ch R = 1 ,13179   ,406.6,433.6,418.3
XS GIS Cut Line= 2
 2351267.6866017670917.6632598172351843.63650589670687.465773379
#Sta/Elev= 30
       0 3000.76    21.5 2991.75    30.7  2988.8    52.2 2984.77    69.4 2982.89
   141.4 2978.36   160.8 2976.27   253.1    2975   265.5 2973.18   280.8 2974.03
   310.7 2973.46   323.6 2974.24   340.8 2973.58  363.352973.861   379.6 2973.36
   385.4 2973.86   401.1 2975.33   422.7    2976   439.9 2975.81   459.3 2977.66
     483 2981.67   491.6 2982.14   504.5 2984.16   533.2    2991   551.6 2996.99
   560.9 2997.61   569.1 3001.06   594.1 3008.68   613.2 3017.25   620.2 3018.53
#Mann= 4 ,-1,0
       0      .1       0     180     .12       0  363.35    .045       0
   385.4      .1       0
Bank Sta=363.35,385.4
XS Rating Curve= 0 ,0
Exp/Cntr(USF)=0,0
Exp/Cntr=0.3,0.1

Type RM Length L Ch R = 1 ,12746   ,236.3,239.8,228.9
XS GIS Cut Line= 2
2351382.53470437671140.9103477292351921.04416318670880.504846066
#Sta/Elev= 30
       0 3007.64     6.3 3005.77      16 3001.73      24 3000.39    54.5 2990.89
    72.9 2986.84    86.2  2982.8   111.8 2976.74   118.8 2975.96   147.8 2975.32
   155.6 2974.64   183.7 2973.75   232.9 2973.97   246.2 2971.63   255.6    2971
  265.382971.652   276.6 2972.14   295.1 2972.04   312.8 2973.29   326.2  2972.1
   342.4 2972.53   366.2  2972.1     375 2970.15   408.3 2972.87   477.2 2974.37
   517.2 2976.49   534.1 2979.69   552.8 2984.49   570.1 2986.67   598.2 2993.13
#Mann= 5 ,-1,0
       0      .1       0   246.2    .045       0  265.38      .1       0
     270     .12       0  598.17      .1       0
Bank Sta=246.2,265.38
XS Rating Curve= 0 ,0
Exp/Cntr(USF)=0,0
Exp/Cntr=0.3,0.1

Type RM Length L Ch R = 1 ,12506   ,223.7,237.3,209.4
XS GIS Cut Line= 4
2351416.97942855671202.9990122822351734.42889846 671155.30665092
2351878.98776584671084.9659969292352027.44044682670905.267120023
#Sta/Elev= 30
       0 3003.31    15.4 2999.86    31.5 2994.78    43.7 2993.15    84.1  2982.7
   104.4  2979.5   197.4 2974.42   225.7 2974.01   254.1 2972.51   318.7 2971.83
   345.2  2970.3   367.4 2970.27   380.7 2969.01   385.2 2968.17  391.222969.038
     399 2970.54   411.9 2969.59   420.8  2970.6   429.7 2969.98   455.6 2970.22
   481.8 2972.55   497.1 2976.58     508 2977.37     523 2976.63   533.4 2977.14
   550.7 2979.93     599 2983.86   673.5 2993.72     689 2994.46   714.9 3001.03
#Mann= 7 ,-1,0
       0      .1       0      10     .12       0     200      .1       0
     210     .12       0   380.7    .045       0  391.22     .12       0
  421.01      .1       0
Bank Sta=380.7,391.22
XS Rating Curve= 0 ,0
Exp/Cntr(USF)=0,0
Exp/Cntr=0.3,0.1

Type RM Length L Ch R = 1 ,12269   ,261.7,282.5,263.8
XS GIS Cut Line= 3
2351457.62335905671312.1601004862351660.41769889671367.200541952
2352136.20788344671129.690271662
#Sta/Elev= 30
       0 2985.97    19.2  2984.5    35.8 2984.84    85.5 2982.06      98 2982.04
   114.6 2980.78   135.3  2980.6   202.4 2977.39   245.6 2977.67   263.5 2975.51
   285.9 2975.24   336.7 2972.74   339.7 2972.41     349 2969.51   366.5 2968.41
   397.6 2969.21   433.4 2968.67   451.3 2969.36   478.1 2969.13   482.8 2968.66
   515.6 2969.14   554.1 2969.03     563 2971.46   584.2 2974.48   635.6 2977.35
   688.2 2983.99   706.5 2987.42     724 2992.62   728.5 2992.91   741.9 2995.72
#Mann= 4 ,-1,0
       0     .12       0  430.13      .1       0   478.1    .045       0
   515.6      .1       0
Bank Sta=478.1,515.6
XS Rating Curve= 0 ,0
Exp/Cntr(USF)=0,0
Exp/Cntr=0.3,0.1

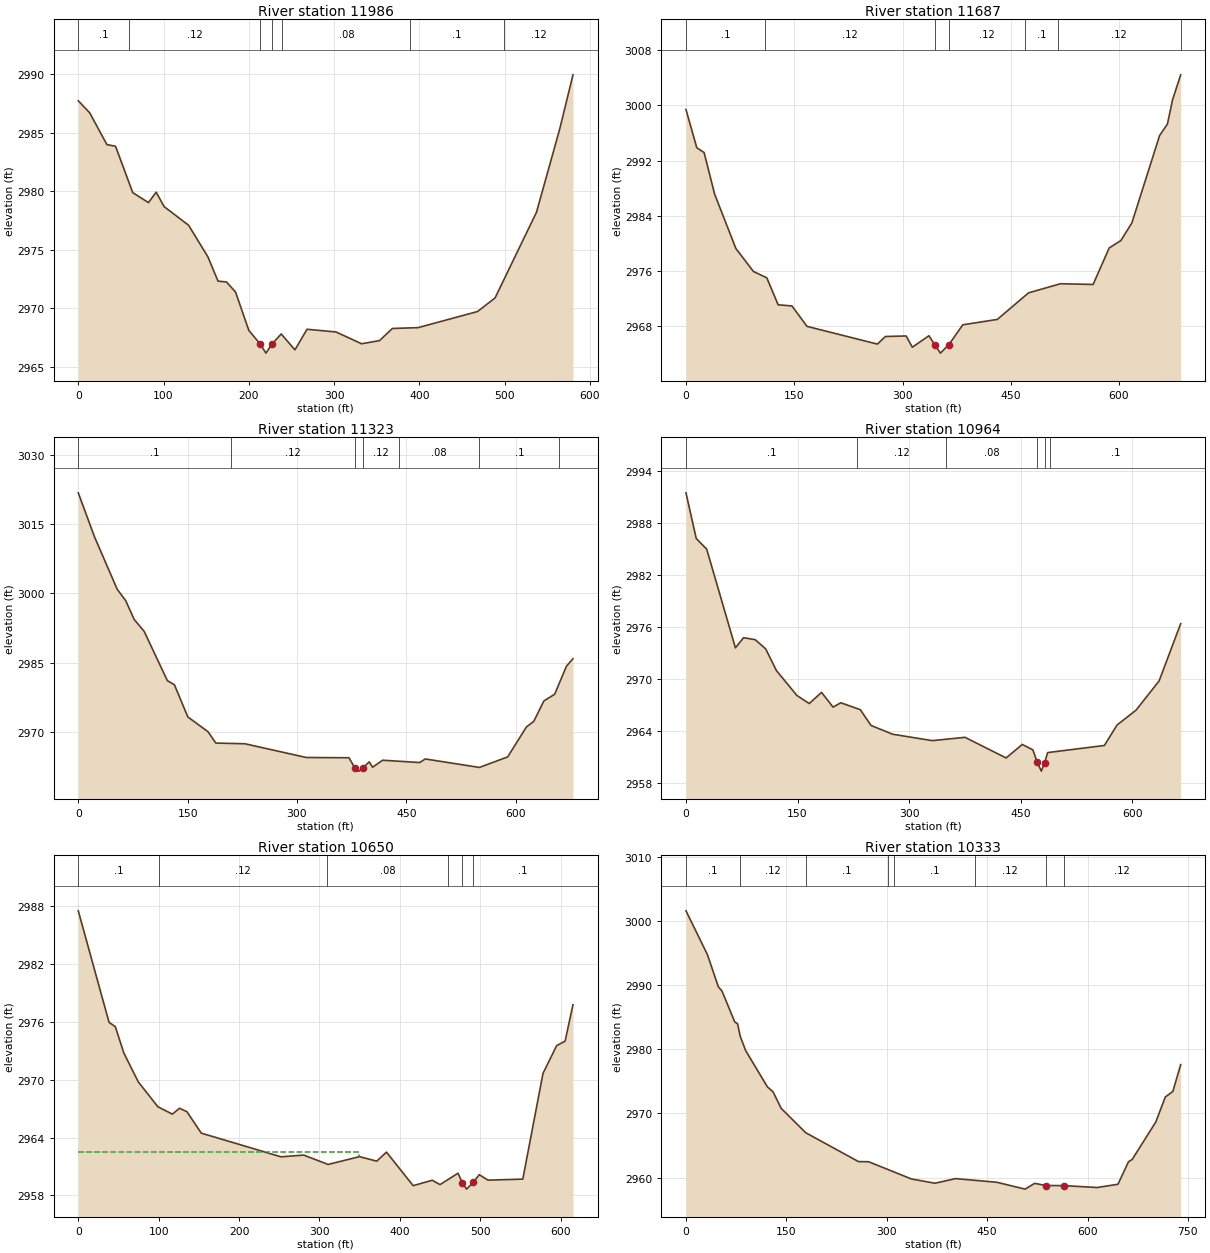
Type RM Length L Ch R = 1 ,11986   ,293.8,298.9,294.2
XS GIS Cut Line= 3
2351798.86236577671664.0114877412351858.02047324671526.763938487
2352179.82965383671240.380374459
#Sta/Elev= 30
       0 2987.75    13.4 2986.72    33.6    2984    43.7 2983.86    63.9 2979.89
    82.3 2979.04    91.4 2979.93   100.6  2978.7   129.4  2977.1   152.1 2974.39
   163.9 2972.32   173.8 2972.25   184.5 2971.38     200 2968.11  213.23 2966.95
   220.1 2966.16   227.3 2966.94     238  2967.8   254.1 2966.44   268.3  2968.2
   302.3 2967.97   332.3 2966.96   353.3 2967.23   368.4 2968.27   398.5 2968.34
   468.3 2969.72   488.8 2970.88   537.4 2978.21   564.6 2985.32   580.2 2989.97
#Mann= 7 ,-1,0
       0      .1       0      60     .12       0  213.23    .045       0
   227.3     .12       0  239.45     .08       0  389.45      .1       0
  499.45     .12       0
Bank Sta=213.23,227.3
XS Rating Curve= 0 ,0
Exp/Cntr(USF)=0,0
Exp/Cntr=0.3,0.1

Type RM Length L Ch R = 1 ,11687   ,358.4,364,357.6
XS GIS Cut Line= 3
2351831.64304393671769.5242978792352220.70368559671496.544138039
2352314.88396928671308.715717226
#Sta/Elev= 30
       0 2999.41      15 2993.86    25.1 2993.17    39.7 2987.14    69.1 2979.26
    93.5 2975.92     112    2975   127.7 2971.09   146.9 2970.92   167.7 2967.96
   265.2 2965.39   276.3 2966.49     305 2966.57   313.6 2964.94   336.6  2966.6
   344.7  2965.3   352.5 2964.08  363.962965.278   383.6 2968.19   431.4 2968.97
   474.6 2972.82   518.7 2974.14   564.1 2974.04   586.4 2979.34   602.6 2980.41
   617.8 2982.97   656.2 2995.64     667 2997.29   674.1  3000.8   685.4 3004.44
#Mann= 7 ,-1,0
       0      .1       0     110     .12       0   344.7    .045       0
  363.96     .12       0     470      .1       0  515.28     .12       0
  685.28      .1       0
Bank Sta=344.7,363.96
XS Rating Curve= 0 ,0
Exp/Cntr(USF)=0,0
Exp/Cntr=0.3,0.1

Type RM Length L Ch R = 1 ,11323   ,356.8,359.6,355.3
XS GIS Cut Line= 2
2351937.69742491672025.4628956372352526.87424993671688.680585114
#Sta/Elev= 30
       0 3021.73    22.5 3012.11    53.5 3000.84    65.1 2998.39    76.6 2994.36
    90.4 2991.75   122.2  2981.1   131.9  2980.2   150.3 2973.24   177.9 2970.06
   188.7 2967.59   228.6 2967.44   312.8 2964.47   371.4 2964.41  379.68 2962.13
   385.3 2961.52   389.9 2962.14   399.1 2963.53   403.7 2962.36   417.5 2963.88
   468.2 2963.38   476.1 2964.15   550.2 2962.32     589 2964.59   614.7 2971.07
   624.8 2972.28   638.7  2976.7   653.5 2978.16   669.6 2984.21   678.6 2985.85
#Mann= 7 ,-1,0
       0      .1       0     210     .12       0  379.68    .045       0
   389.9     .12       0     440     .08       0     550      .1       0
     660     .12       0
Bank Sta=379.68,389.9
XS Rating Curve= 0 ,0
Exp/Cntr(USF)=0,0
Exp/Cntr=0.3,0.1

Type RM Length L Ch R = 1 ,10964   ,310.7,313.4,312
XS GIS Cut Line= 2
2352172.83237541672321.4143410532352630.79764244671838.892704972
#Sta/Elev= 30
       0 2991.44    13.8 2986.17    27.9 2984.93    66.5 2973.55    77.5 2974.72
    93.1 2974.49   107.2 2973.43   121.6 2970.93   149.2 2968.05   165.8 2967.12
   182.3 2968.41   197.8 2966.71   208.2 2967.21   234.5 2966.41   248.9 2964.59
   277.9 2963.58   331.2 2962.84   375.3 2963.22   430.5 2960.84   452.3  2962.4
   466.6 2961.77   472.2 2960.38   477.9 2959.32  482.452960.315   486.4 2961.46
   562.7 2962.28   579.7 2964.64   605.2 2966.35   636.3 2969.73   665.3 2976.34
#Mann= 6 ,-1,0
       0      .1       0     230     .12       0     350     .08       0
   472.2    .045       0  482.45     .08       0     490      .1       0
Bank Sta=472.2,482.45
XS Rating Curve= 0 ,0
Exp/Cntr(USF)=0,0
Exp/Cntr=0.3,0.1

Type RM Length L Ch R = 1 ,10650   ,315.8,316.9,310.2
XS GIS Cut Line= 2
2352337.57148868672458.4857780222352799.54281074672051.927792624
#Sta/Elev= 30
       0 2987.53    38.3 2975.96    46.1 2975.51    56.6  2972.8    74.6 2969.79
    99.1  2967.2     117 2966.44     126 2967.05   135.2 2966.69     153 2964.47
   252.2 2962.01   280.5 2962.19   310.8 2961.22   349.8 2962.03   371.3 2961.56
   383.4  2962.5   416.6 2959.02   440.4 2959.58     450 2959.13   472.4 2960.31
   477.7 2959.34     483 2958.66  491.482959.366   498.8 2960.16   509.7 2959.59
     553  2959.7   578.1 2970.66   595.1 2973.55   605.6 2974.01   615.4 2977.79
#Mann= 6 ,-1,0
       0      .1       0     100     .12       0     310     .08       0
     460      .1       0   477.7    .045       0  491.48      .1       0
#XS Ineff= 2 , 0
          349.57 2962.48
Permanent Ineff=
       F       F
Bank Sta=477.7,491.48
XS Rating Curve= 0 ,0
Exp/Cntr(USF)=0,0
Exp/Cntr=0.3,0.1

Type RM Length L Ch R = 1 ,10333   ,240.2,242.5,233.7
XS GIS Cut Line= 3
2352436.71047897672665.2504862812352624.19959453672627.179507012
2352999.93079368672228.481268025
#Sta/Elev= 30
       0 3001.59    32.1 2994.75    48.4 2989.74    53.9 2989.07    72.9 2984.26
      77    2984    81.1 2982.02    89.2  2979.8   121.7 2974.14   130.1 2973.37
   142.3 2970.79     179 2966.99   257.8 2962.49   272.9 2962.47     337 2959.78
   372.1 2959.12   402.9 2959.84   464.4 2959.27   506.8  2958.2     521  2959.1
   537.9 2958.76   564.5 2958.75   614.3 2958.45   645.5 2958.96   661.3 2962.48
   666.7 2962.82   702.1 2968.68   716.2 2972.56   727.5 2973.43   739.2 2977.61
#Mann= 8 ,-1,0
       0      .1       0      80     .12       0     180      .1       0
  301.32     .12       0  311.32      .1       0  431.32     .12       0
   537.9    .045       0   564.5     .12       0
Bank Sta=537.9,564.5
XS Rating Curve= 0 ,0
Exp/Cntr(USF)=0,0
Exp/Cntr=0.3,0.1

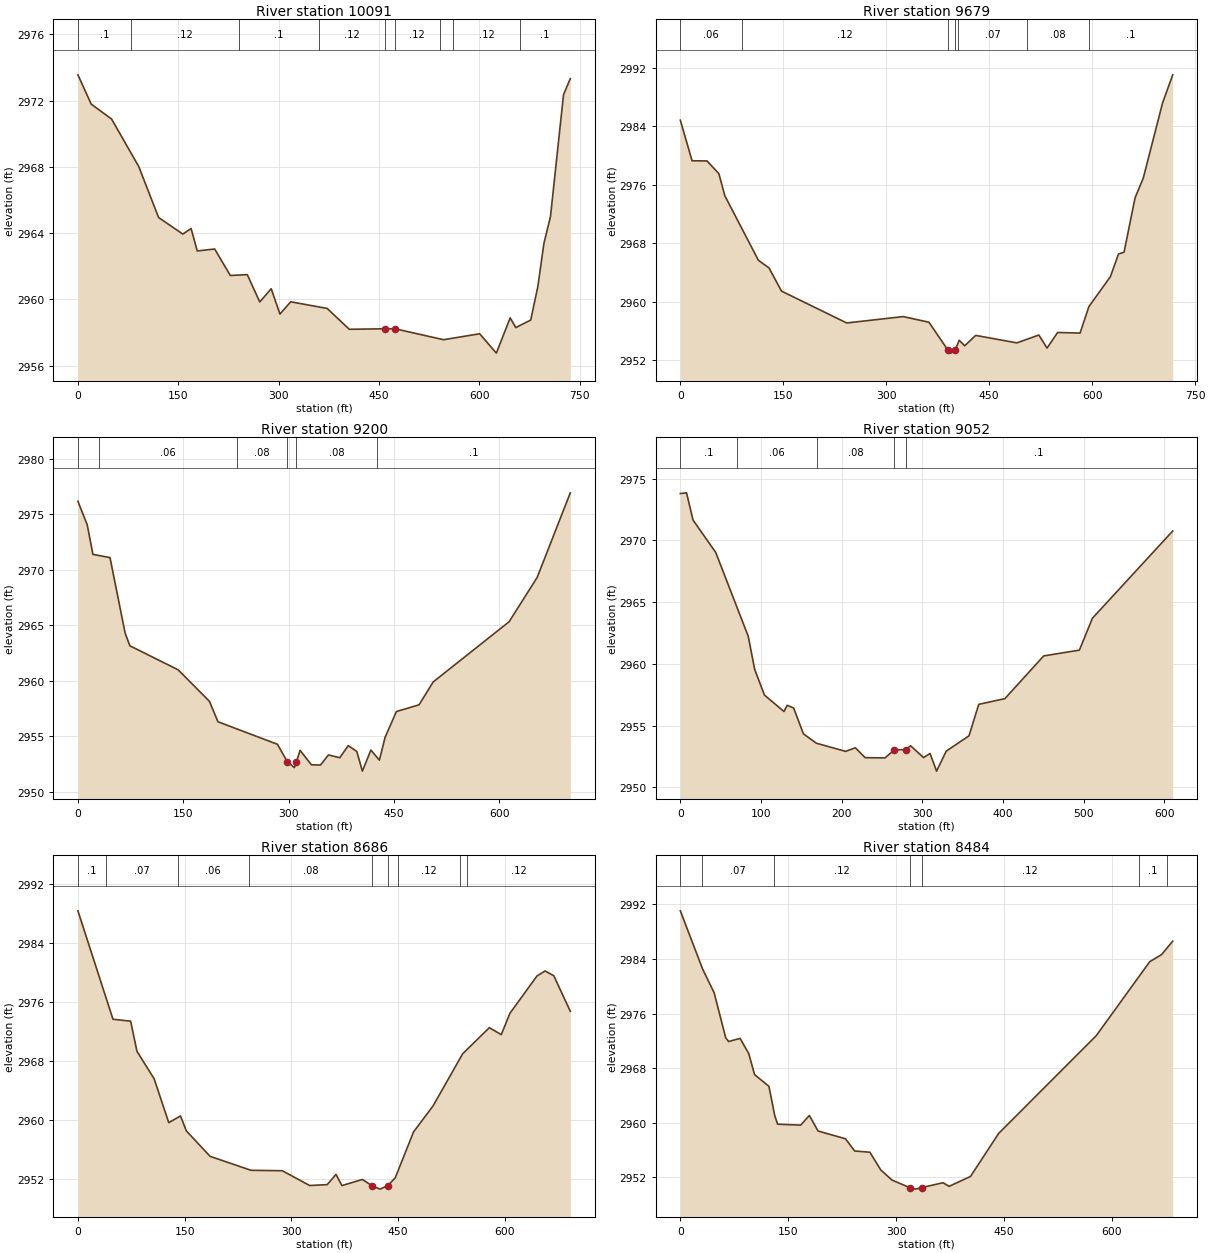
Type RM Length L Ch R = 1 ,10091   ,408.4,412.2,409.7
XS GIS Cut Line= 4
2352708.48735781672890.7517710422352937.55966732672712.356471504
2353042.43544372672325.0742369722353067.66751874672288.831162421
#Sta/Elev= 30
       0 2973.56    19.9 2971.79    50.3 2970.89    90.9 2968.02   120.6 2964.94
   156.8 2963.94   169.1 2964.28   178.3 2962.92   204.4 2963.04   227.7 2961.44
   253.1 2961.49   271.7 2959.84   288.8 2960.64   301.9 2959.11   317.9 2959.85
   372.4 2959.45   405.5 2958.19   459.4 2958.22  473.97 2958.22   546.4 2957.56
   600.3 2957.92   625.2 2956.75   645.9 2958.88   654.2 2958.29   676.6 2958.75
   687.3 2960.79   696.3 2963.38   706.1    2965   725.6 2972.36   735.7 2973.33
#Mann= 9 ,-1,0
       0      .1       0      80     .12       0     240      .1       0
  360.34     .12       0   459.4    .045       0  473.97     .12       0
  540.34     .08       0  560.34     .12       0  660.34      .1       0
Bank Sta=459.4,473.97
XS Rating Curve= 0 ,0
Exp/Cntr(USF)=0,0
Exp/Cntr=0.3,0.1

Type RM Length L Ch R = 1 ,9679    ,471.3,479.1,476.1
XS GIS Cut Line= 4
2353473.10205029673020.9699554412353340.67543847672702.542615683
2353349.49665038672437.8399834082353342.28902786672330.382324896
#Sta/Elev= 30
       0 2984.81    17.1 2979.27    38.8 2979.25    56.1 2977.52    64.8  2974.5
   113.8 2965.67   129.1 2964.65   147.4 2961.47   242.4 2957.12   324.7 2957.99
   362.2 2957.22  389.43 2953.47   394.3    2953   400.6 2953.45   406.3 2954.76
   414.3    2954   430.3 2955.42   490.3  2954.4   522.3 2955.47   534.3 2953.69
   549.7 2955.82   582.4 2955.74   595.2 2959.34   626.6 2963.45   638.4 2966.54
   646.5 2966.79   662.5  2974.2   674.5 2976.91   702.6 2987.17   717.4 2991.01
#Mann= 7 ,-1,0
       0     .06       0      90     .12       0  389.43    .045       0
   400.6     .12       0  404.87     .07       0  504.87     .08       0
  594.87      .1       0
Bank Sta=389.43,400.6
XS Rating Curve= 0 ,0
Exp/Cntr(USF)=0,0
Exp/Cntr=0.3,0.1

Type RM Length L Ch R = 1 ,9200    ,144.5,147.4,144.8
XS GIS Cut Line= 4
 2353644.8887574672966.3650532922353672.58097266672782.036946684
2353711.91194945 672476.893173812353702.40734526672270.183256933
#Sta/Elev= 30
       0 2976.17    13.3 2974.04    21.4 2971.38    45.7 2971.09    67.2 2964.29
      74 2963.14   142.8 2960.97   187.3 2958.13   199.4 2956.29   284.1 2954.26
   298.12952.692   308.2 2952.16  311.15 2952.68   316.3 2953.71   332.5 2952.41
   345.3 2952.39   356.7  2953.3   372.8 2953.05   384.9 2954.14     397 2953.62
     405 2951.84   417.1 2953.74   429.2 2952.83   437.3 2954.88   453.4 2957.21
   485.7 2957.82   505.8 2959.88   613.9 2965.31   653.9 2969.31     701 2976.93
#Mann= 6 ,-1,0
       0      .1       0      30     .06       0   226.4     .08       0
   298.1    .045       0  311.15     .08       0   426.4      .1       0
Bank Sta=298.1,311.15
XS Rating Curve= 0 ,0
Exp/Cntr(USF)=0,0
Exp/Cntr=0.3,0.1

Type RM Length L Ch R = 1 ,9052    ,352.1,366.4,362.1
XS GIS Cut Line= 2
2353849.22603251672916.8286648282353780.63378554672310.218785363
#Sta/Elev= 30
       0  2973.8     7.7 2973.86    15.7 2971.66    43.9 2969.03    84.2 2962.24
    92.2 2959.55   104.3 2957.48   128.5 2956.15   132.5 2956.65   140.5 2956.43
   152.6 2954.34   168.7 2953.58   204.9 2952.92     217 2953.21   229.1 2952.41
   253.8 2952.39   265.3 2953.05  279.292953.059   285.5 2953.37   301.6 2952.42
   309.6 2952.75   317.7 2951.32   329.7 2952.94   357.9 2954.18     370 2956.73
   402.4 2957.19   450.5 2960.65   494.8 2961.12   510.9  2963.7   610.5 2970.77
#Mann= 5 ,-1,0
       0      .1       0      70     .06       0     170     .08       0
   265.3    .045       0  279.29      .1       0
Bank Sta=265.3,279.29
XS Rating Curve= 0 ,0
Exp/Cntr(USF)=0,0
Exp/Cntr=0.3,0.1

Type RM Length L Ch R = 1 ,8686    ,192.9,201.9,199.7
XS GIS Cut Line= 4
2354117.18580629672880.9850009892353998.20208579672408.789585911
2353949.68273044672246.1094052342353918.70892343672263.133621295
#Sta/Elev= 30
       0 2988.37    49.3 2973.69    74.1 2973.43      83 2969.35   107.1 2965.64
   127.7 2959.69   144.2  2960.6   152.4 2958.58   185.8 2955.13   243.2 2953.24
   287.3 2953.18   325.7 2951.18   350.4  2951.3   362.8 2952.68   371.1 2951.17
   399.9    2952   413.4 2951.15   424.7 2950.69   435.6 2951.16   446.1 2952.23
   471.8 2958.44   499.1 2961.94   540.8 2969.01   578.3 2972.55   595.1 2971.61
   607.2 2974.49   645.2 2979.54   656.7 2980.23   668.9 2979.58   692.1 2974.77
#Mann= 9 ,-1,0
       0      .1       0      40     .07       0     140     .06       0
     240     .08       0   413.4    .045       0   435.6     .08       0
     450     .12       0  536.96      .1       0  546.96     .12       0
Bank Sta=413.4,435.6
XS Rating Curve= 0 ,0
Exp/Cntr(USF)=0,0
Exp/Cntr=0.3,0.1

Type RM Length L Ch R = 1 ,8484    ,261.7,269.7,263.5
XS GIS Cut Line= 4
2354238.56253349672872.0503388432354223.81922555 672682.49108593
2354118.77238669672383.2709791142354080.85949798672209.914377868
#Sta/Elev= 30
       0 2991.07      31 2982.53      47 2979.06    63.1 2972.46    67.1 2971.91
    83.1 2972.37    95.2 2970.12   103.2 2967.06   123.2 2965.34   131.3 2961.03
   135.3 2959.79   167.4 2959.65   179.4 2961.07   191.5 2958.79   229.7 2957.65
   242.4 2955.86   263.6 2955.68   278.7 2953.08   294.4 2951.59   318.9  2950.5
   327.2 2950.27   335.7  2950.5   365.3 2951.21   373.8 2950.68   403.5 2952.13
   442.6 2958.43   578.4 2972.77   652.7 2983.61   669.1 2984.65   684.7 2986.62
#Mann= 7 ,-1,0
       0      .1       0      30     .07       0     130     .12       0
   318.9    .045       0   335.7     .12       0  637.26      .1       0
  677.26     .12       0
Bank Sta=318.9,335.7
XS Rating Curve= 0 ,0
Exp/Cntr(USF)=0,0
Exp/Cntr=0.3,0.1

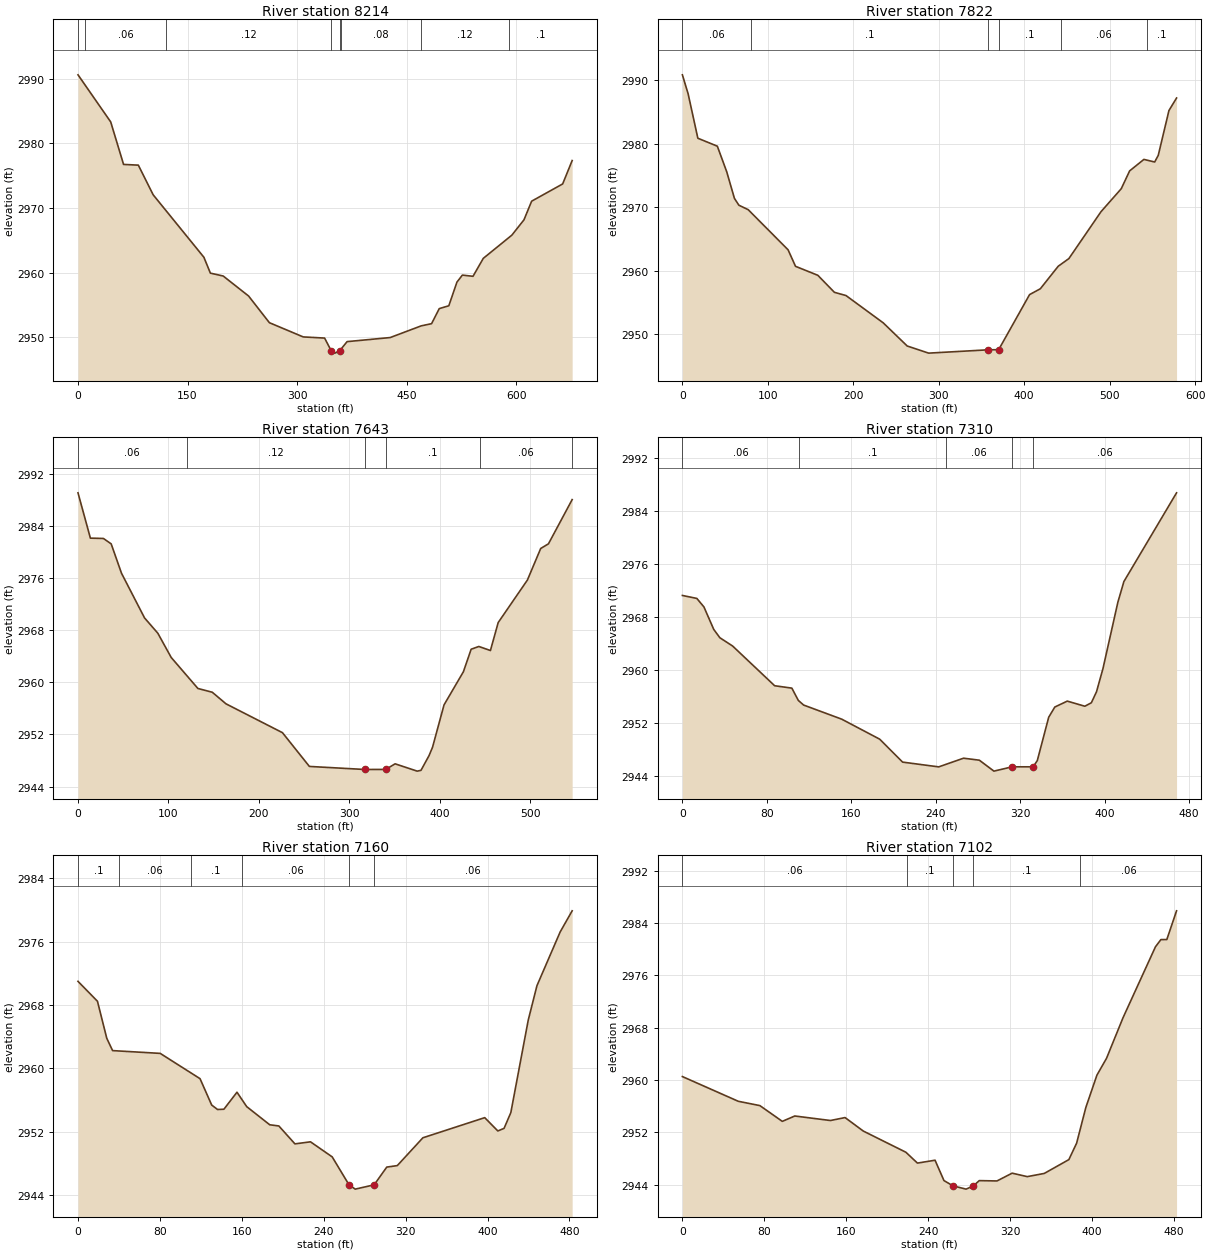
Type RM Length L Ch R = 1 ,8214    ,387.8,392.2,387.4
XS GIS Cut Line= 2
2354572.25521058672751.128988126 2354212.1972165672178.138994173
#Sta/Elev= 30
       0 2990.62    44.8 2983.33    62.4 2976.75    82.6 2976.64     103 2972.04
   172.4 2962.38   181.3 2959.92   198.8 2959.48   233.6 2956.38   262.1 2952.25
   308.4 2950.05   337.7 2949.87   346.7 2947.92   351.9 2947.54  358.41 2947.92
   368.5 2949.32   427.5 2949.95     470 2951.76   484.2  2952.1   494.7 2954.43
   507.8 2954.87   518.9 2958.53   526.4 2959.62   540.9 2959.43     555 2962.21
   594.1  2965.8   610.7 2968.17   621.2 2971.06   663.7 2973.73   676.7 2977.35
#Mann= 8 ,-1,0
       0     .07       0      10     .06       0     120     .12       0
   346.7    .045       0  358.41     .12       0     360     .08       0
     470     .12       0     590      .1       0
Bank Sta=346.7,358.41
XS Rating Curve= 0 ,0
Exp/Cntr(USF)=0,0
Exp/Cntr=0.3,0.1

Type RM Length L Ch R = 1 ,7822    ,171.2,178.5,170.9
XS GIS Cut Line= 3
2354816.21515268672510.4609038222354577.81937699672197.527439107
2354523.85560634672020.646026656
#Sta/Elev= 30
       0 2990.85     6.7 2987.87    18.1 2980.87    40.9 2979.62    51.9 2975.59
    60.9 2971.41    66.1 2970.33      77 2969.63   123.7 2963.31   132.4 2960.71
   158.5  2959.3   177.9 2956.62   191.5 2956.11     235 2951.82   263.1 2948.17
   288.2 2947.05   357.7 2947.57  370.132947.592   406.3 2956.26   418.9 2957.18
   439.8 2960.72   452.3 2961.93   489.9 2969.31   513.6 2972.93   523.4 2975.73
   540.1 2977.54   552.7 2977.13   556.9 2978.18   569.4 2985.23   578.3  2987.2
#Mann= 6 ,-1,0
       0     .06       0      80      .1       0   357.7    .045       0
  370.13      .1       0   443.4     .06       0   543.4      .1       0
Bank Sta=357.7,370.13
XS Rating Curve= 0 ,0
Exp/Cntr(USF)=0,0
Exp/Cntr=0.3,0.1

Type RM Length L Ch R = 1 ,7643    ,329.9,333.5,315.1
XS GIS Cut Line= 4
2354907.49511641672445.0036710492354775.67891671672260.928977981
 2354714.8406707672093.2338126852354664.92210986671960.637635474
#Sta/Elev= 30
       0 2989.07    13.7 2982.12    28.1 2982.07    36.7 2981.24    48.1 2976.74
    73.6 2969.88    88.3 2967.53   103.1 2963.81   132.6 2959.06   148.5 2958.48
   163.7  2956.7   226.1 2952.28   255.9  2947.1  317.48 2946.63   340.3 2946.64
   350.7  2947.5   375.1 2946.38   379.3  2946.5   388.2 2948.75   392.1 2950.05
   404.8 2956.54   426.2 2961.62   434.8 2965.08   443.3  2965.5   456.1 2964.88
   464.7 2969.17     497 2975.69   511.7 2980.53   520.3 2981.25   546.5 2988.03
#Mann= 6 ,-1,0
       0     .06       0     120     .12       0  317.48    .045       0
   340.3      .1       0  444.79     .06       0  546.48      .1       0
Bank Sta=317.48,340.3
XS Rating Curve= 0 ,0
Exp/Cntr(USF)=0,0
Exp/Cntr=0.3,0.1

Type RM Length L Ch R = 1 ,7310    ,150.6,149.7,138.4
XS GIS Cut Line= 2
2355146.86727689672229.8018920482354809.59874081671905.243491533
#Sta/Elev= 30
       0 2971.31    13.7 2970.86    20.4 2969.58    29.7 2966.19    35.5 2964.93
    47.6 2963.68    87.4 2957.69   103.7 2957.33   109.8 2955.48   114.8 2954.78
   150.9 2952.65   186.9 2949.63   208.6 2946.17   242.8 2945.45   266.3 2946.76
   281.3 2946.46   295.1 2944.81   312.4 2945.46  332.26 2945.46   336.2  2946.4
     347 2952.94   352.8 2954.48   364.6 2955.37   381.2  2954.6   387.4 2955.12
   392.3 2956.79   398.4 2960.28   412.5 2970.28   418.2  2973.4   468.1 2986.79
#Mann= 5 ,-1,0
       0     .06       0     110      .1       0     250     .06       0
   312.4    .045       0  332.26     .06       0
Bank Sta=312.4,332.26
XS Rating Curve= 0 ,0
Exp/Cntr(USF)=0,0
Exp/Cntr=0.3,0.1

Type RM Length L Ch R = 1 ,7160    ,58.7,58.8,59.6
XS GIS Cut Line= 6
 2355228.8462659672184.052046658 2355116.9833604672043.351301094
2355089.81674362672005.4443939622354987.46809436671963.746796117
2354945.77049652 671961.85145076 2354867.3780071671893.434677585
#Sta/Elev= 30
       0 2970.99      19 2968.48    28.1 2963.81    33.8 2962.25    80.3  2961.9
   119.2 2958.71   130.6 2955.38   136.3 2954.82   142.5 2954.85   155.3    2957
   164.8 2955.18   187.3 2952.89   196.2 2952.74   211.9 2950.48   227.1 2950.74
   248.3 2948.84   264.7 2945.32   270.8 2944.77   289.32945.313   301.6 2947.55
   311.9 2947.74   336.9 2951.25   397.3 2953.79   410.1 2952.11   416.2 2952.44
   422.8 2954.43   439.8  2966.1   448.3 2970.44     471 2977.23   482.7 2979.89
#Mann= 6 ,-1,0
       0      .1       0      40     .06       0     110      .1       0
     160     .06       0   264.7    .045       0   289.3     .06       0
Bank Sta=264.7,289.3
XS Rating Curve= 0 ,0
Exp/Cntr(USF)=0,0
Exp/Cntr=0.3,0.1

Type RM Length L Ch R = 1 ,7102    ,163.2,178.3,174.3
XS GIS Cut Line= 6
2355258.13716851672133.553861358  2355146.274263671992.853115794
2355119.10764622671954.9462086622355016.75899697671913.248610817
2354975.06139912671911.353265461 2354896.6689097671842.936492285
#Sta/Elev= 30
       0 2960.52    54.6 2956.74    75.7 2956.08    97.6 2953.67   109.8 2954.49
   144.6  2953.8   158.9 2954.25   176.7 2952.19   218.3 2948.95   229.6 2947.29
   246.8 2947.73   255.5 2944.62   264.32943.811   277.1 2943.31   284.1 2943.79
     290 2944.61   307.3 2944.56   322.1 2945.75   336.9 2945.22   353.5 2945.71
   377.5 2947.82   385.1 2950.34   394.1  2955.8   404.9 2960.73   414.3 2963.31
   430.4 2969.51   462.1 2980.36   467.4 2981.46   473.2 2981.47   482.7 2985.86
#Mann= 5 ,-1,0
       0     .06       0  219.75      .1       0   264.3    .045       0
   284.1      .1       0  388.64     .06       0
Bank Sta=264.3,284.1
XS Rating Curve= 0 ,0
Exp/Cntr(USF)=0,0
Exp/Cntr=0.3,0.1

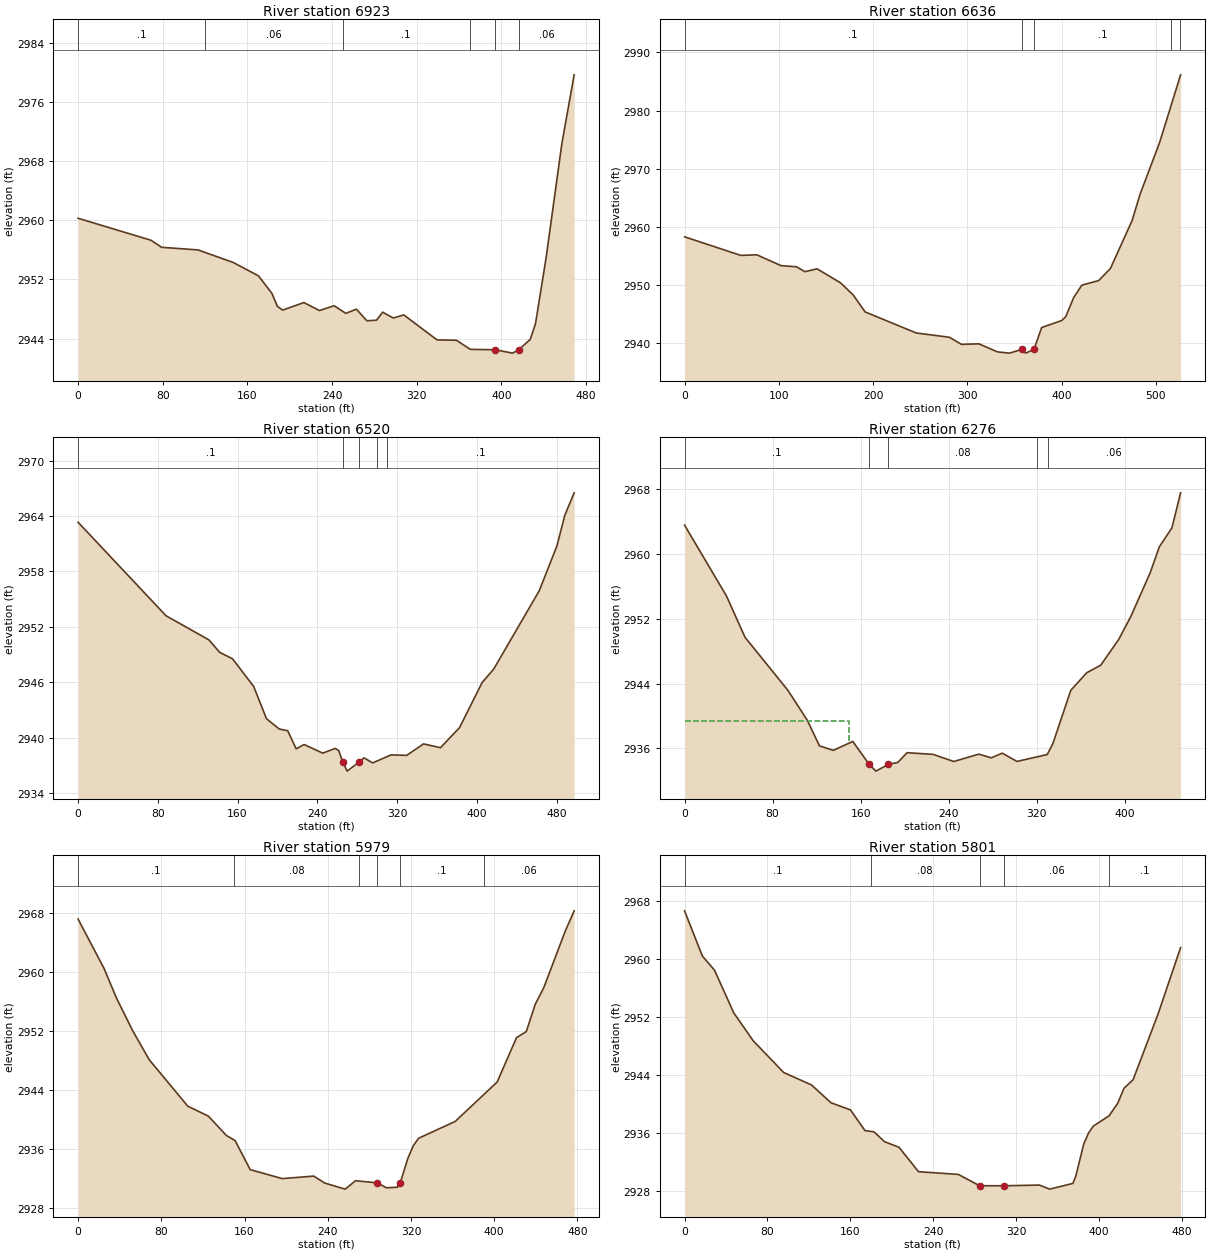
Type RM Length L Ch R = 1 ,6923    ,276.7,287.6,289.3
XS GIS Cut Line= 2
2355359.40317254672052.4780161962354982.85542507671773.210781873
#Sta/Elev= 30
       0 2960.28    68.8 2957.31      79 2956.35   113.3    2956   146.5 2954.31
   170.5 2952.49   183.3 2950.09   188.3 2948.37   193.3 2947.86   213.4 2948.88
   228.1  2947.8     242 2948.45     253 2947.42     263 2947.99   272.9 2946.42
     282 2946.49   287.9 2947.58   297.8 2946.79   307.8 2947.21   339.2 2943.83
   357.6 2943.78   370.7 2942.55   394.22942.498   410.7 2942.04   416.4  2942.5
   427.3 2943.89   432.3 2946.04   442.3 2954.93   457.2 2970.38   468.8 2979.68
#Mann= 6 ,-1,0
       0      .1       0     120     .06       0     250      .1       0
     370     .06       0   394.2    .045       0   416.4     .06       0
Bank Sta=394.2,416.4
XS Rating Curve= 0 ,0
Exp/Cntr(USF)=0,0
Exp/Cntr=0.3,0.1

Type RM Length L Ch R = 1 ,6636    ,115.8,116.1,114.1
XS GIS Cut Line= 3
2355388.09774861672013.3093899862355242.66782141671612.921973282
2355155.30800002671563.614134842
#Sta/Elev= 30
       0 2958.26    59.7 2955.06    76.7 2955.16   102.3  2953.3   118.7  2953.1
   127.8 2952.26   140.6 2952.75   165.5 2950.34   178.9 2948.26   191.6 2945.33
   245.8 2941.71     281 2940.97   293.8 2939.75   312.2 2939.84   332.1 2938.45
   344.8 2938.24   357.6 2938.87   361.9 2938.24  370.71 2938.88   378.9 2942.65
   400.2 2943.85   404.4 2944.51   412.9 2947.82   421.5 2949.94   439.4 2950.73
   451.8  2952.8   474.8 2961.04   483.4 2965.64     504 2974.48   526.3 2986.14
#Mann= 5 ,-1,0
       0      .1       0   357.6    .045       0  370.71      .1       0
  515.98     .06       0  525.98      .1       0
Bank Sta=357.6,370.71
XS Rating Curve= 0 ,0
Exp/Cntr(USF)=0,0
Exp/Cntr=0.3,0.1

Type RM Length L Ch R = 1 ,6520    ,242.6,243.2,232.7
XS GIS Cut Line= 4
2355525.73994443671904.7653686692355421.50029748671810.881952978
2355338.04270359 671583.128519182355269.03511039671491.361778056
#Sta/Elev= 30
       0 2963.33    88.2  2953.2   131.3 2950.58   142.1 2949.23   154.9 2948.54
   176.2 2945.53     189 2942.04   201.7 2940.93   210.3 2940.74   218.8 2938.78
   226.8 2939.24   245.5 2938.31     258 2938.82   261.4  2938.6   265.72937.346
   269.9 2936.36   282.1 2937.35   286.9  2937.8   295.5 2937.25   314.1 2938.12
   329.7 2938.07   346.6 2939.31   363.6  2938.9   382.7 2941.07   405.3 2945.95
     417 2947.42   462.7 2955.91   480.4 2960.76   488.4 2964.11   497.7 2966.52
#Mann= 5 ,-1,0
       0      .1       0   265.7    .045       0   282.1      .1       0
  300.29     .08       0  310.29      .1       0
Bank Sta=265.7,282.1
XS Rating Curve= 0 ,0
Exp/Cntr(USF)=0,0
Exp/Cntr=0.3,0.1

Type RM Length L Ch R = 1 ,6276    ,287.3,297.7,289.1
XS GIS Cut Line= 2
2355690.35087273671688.7810962122355358.75883337671383.371291206
#Sta/Elev= 30
       0 2963.58    38.1 2954.82      55 2949.71    93.9 2943.17   111.7 2939.43
   122.6  2936.3   135.2 2935.75   152.9 2936.85  167.682934.031   173.9 2933.18
   185.3 2934.02   193.8 2934.25   202.2 2935.46   225.9 2935.25   244.7 2934.37
   267.4 2935.28   278.7 2934.82   288.7  2935.4   302.1 2934.38   329.6 2935.23
   334.7 2936.57     351 2943.17   365.5 2945.34   378.2 2946.27   394.5 2949.44
   405.4 2952.25     423 2957.64   431.5 2960.91   442.9 2963.24   450.8 2967.57
#Mann= 5 ,-1,0
       0      .1       0  167.68    .045       0   185.3     .08       0
     320      .1       0     330     .06       0
#XS Ineff= 2 , 0
          149.82 2939.41
Permanent Ineff=
       F       F
Bank Sta=167.68,185.3
XS Rating Curve= 0 ,0
Exp/Cntr(USF)=0,0
Exp/Cntr=0.3,0.1

Type RM Length L Ch R = 1 ,5979    ,176.4,177.7,174.8
XS GIS Cut Line= 2
2355867.99713529671513.2940495032355489.33806894671223.464685101
#Sta/Elev= 30
       0 2967.21      25 2960.49      37 2956.45    52.8 2951.96    68.4  2948.1
   105.5 2941.79   125.2 2940.45   142.6 2937.81   150.9 2937.13   165.4 2933.18
   196.2 2931.96   226.5  2932.3   237.1 2931.35   256.7 2930.53   266.7 2931.67
   287.7 2931.38   296.3 2930.71     307 2930.79  309.612931.367   317.1 2934.76
   322.2 2936.42   327.2 2937.43   362.5 2939.73   402.8 2945.08   421.4  2951.1
   430.8 2951.93   439.4 2955.63   447.7 2957.92   468.2 2965.56   476.8 2968.33
#Mann= 6 ,-1,0
       0      .1       0     150     .08       0     270      .1       0
   287.7    .045       0  309.61      .1       0     390     .06       0
Bank Sta=287.7,309.61
XS Rating Curve= 0 ,0
Exp/Cntr(USF)=0,0
Exp/Cntr=0.3,0.1

Type RM Length L Ch R = 1 ,5801    ,367.9,380,373.1
XS GIS Cut Line= 2
2356004.68984148 671364.350193982355596.41770693671113.830791131
#Sta/Elev= 30
       0 2966.66    17.2 2960.41    28.9 2958.47    47.5 2952.57    66.3 2948.71
    95.7 2944.33   122.6 2942.61   141.4 2940.15   160.2 2939.16   174.2 2936.31
     183 2936.13     193 2934.78   207.1    2934   225.9 2930.63   264.4 2930.25
   284.8 2928.69   308.32928.683   342.6 2928.78   352.6 2928.22     375 2929.01
   377.9 2930.06   385.4 2934.43   390.1 2935.97   394.8 2936.94   409.9 2938.34
   418.3 2940.09   424.4 2942.17   433.1 2943.32   457.3 2952.44     479 2961.59
#Mann= 5 ,-1,0
       0      .1       0     180     .08       0   284.8    .045       0
   308.3     .06       0     410      .1       0
Bank Sta=284.8,308.3
XS Rating Curve= 0 ,0
Exp/Cntr(USF)=0,0
Exp/Cntr=0.3,0.1