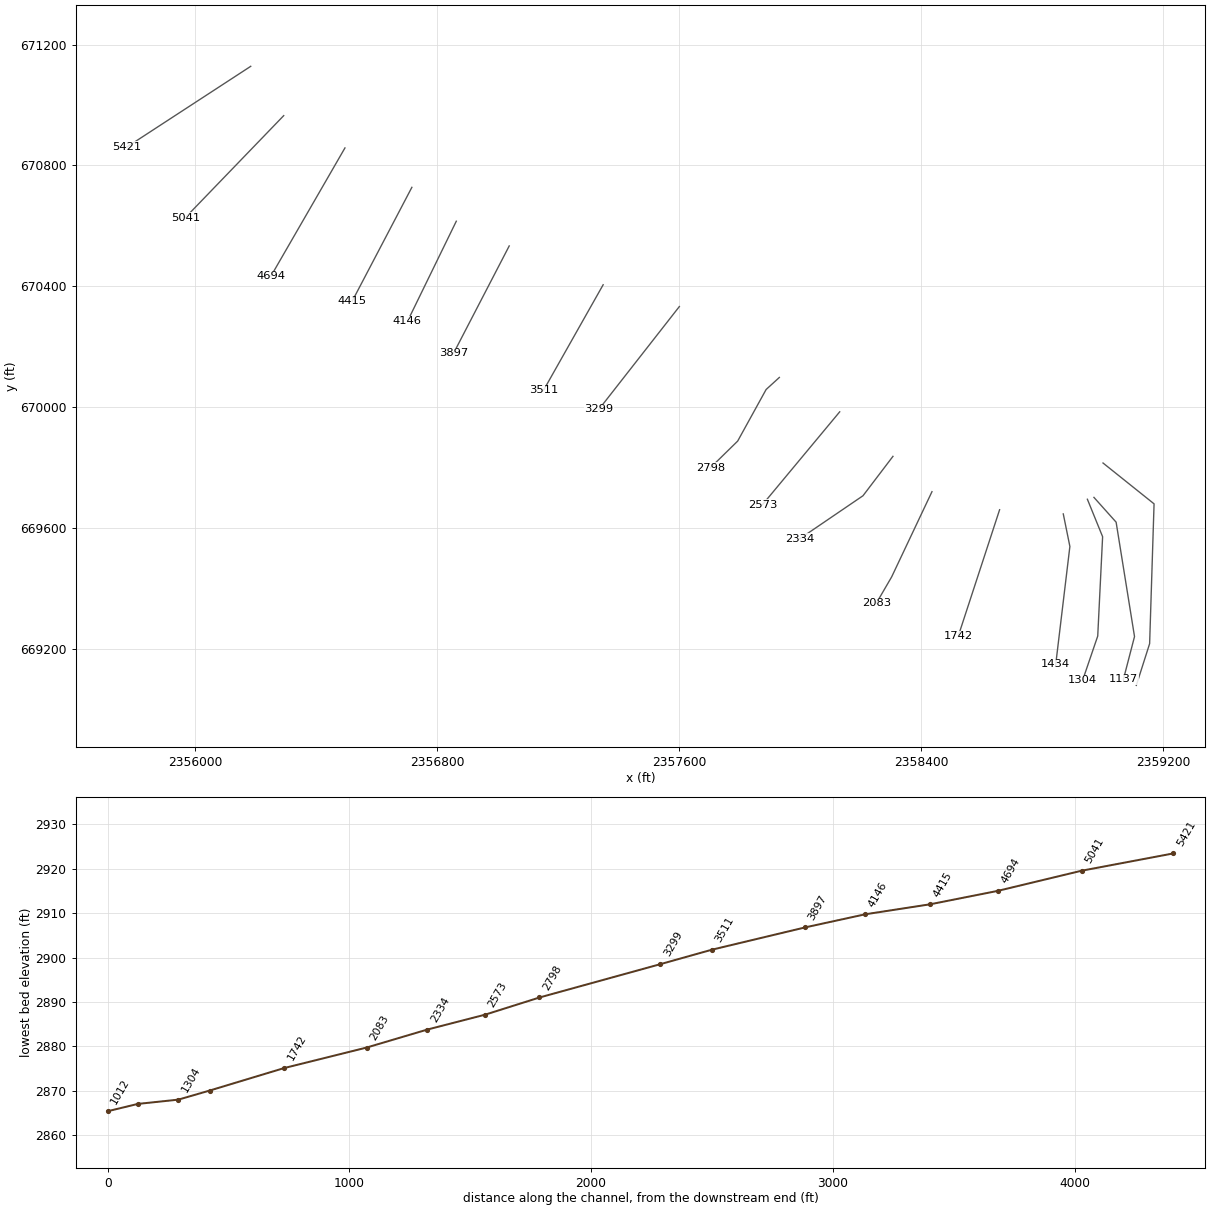
HEC-RAS study BEAVERDMRN.prj: BEAVERDMRN

--- BEAVERDMRN.g01 (geometry) --- (continued)

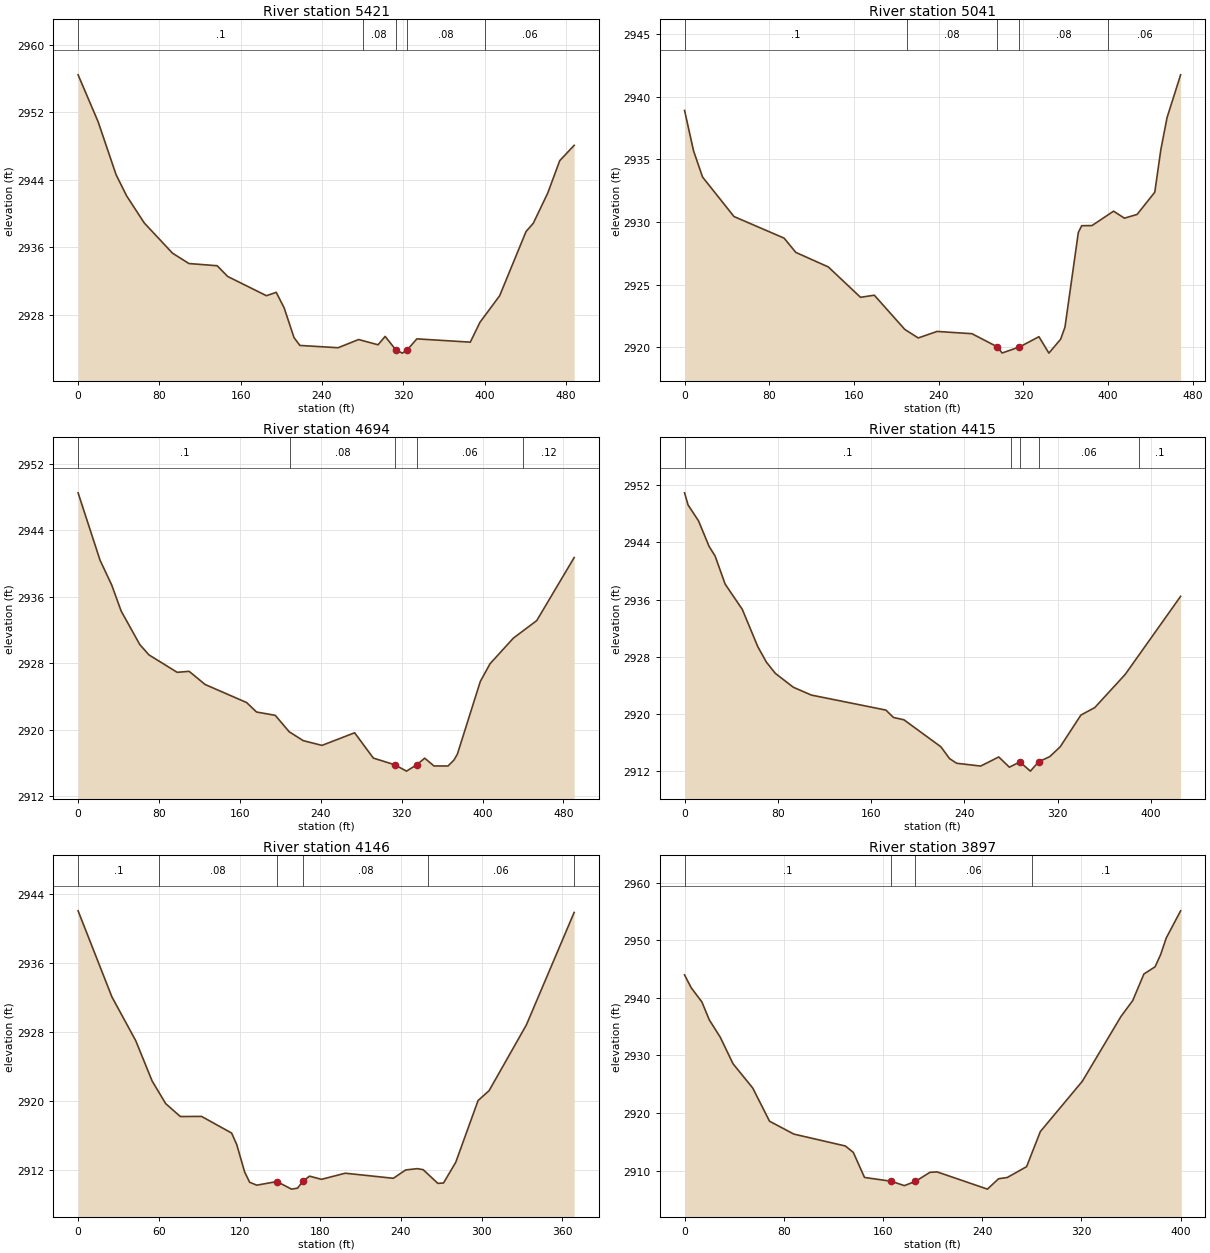
Type RM Length L Ch R = 1 ,5421    ,380,380,380
XS GIS Cut Line= 2
2356183.54629795671127.9077970112355774.50173091 670861.40679378
#Sta/Elev= 30
       0 2956.41    19.7 2950.86    37.4 2944.58    47.8 2942.07    65.1 2938.87
    92.9 2935.29   109.1 2934.06   136.9  2933.8   147.2 2932.53   185.4 2930.25
     195 2930.65   202.8 2928.81   212.5 2925.29   218.3 2924.36   255.9 2924.09
   276.1 2925.06   295.2 2924.44   302.2 2925.43  312.71 2923.84   319.1 2923.45
   323.9 2923.83   333.4 2925.14     386 2924.75   395.5  2927.1   414.9 2930.25
   440.9 2937.86     448 2938.83   462.3 2942.43     474 2946.24   488.2 2948.06
#Mann= 5 ,-1,0
       0      .1       0     280     .08       0  312.71    .045       0
   323.9     .08       0     400     .06       0
Bank Sta=312.71,323.9
XS Rating Curve= 0 ,0
Exp/Cntr(USF)=0,0
Exp/Cntr=0.3,0.1

Type RM Length L Ch R = 1 ,5041    ,347,347,347
XS GIS Cut Line= 2
2356292.56609184670964.8300965212355967.30899861670627.626800063
#Sta/Elev= 30
       0  2938.9     8.5 2935.68      17 2933.59    46.7 2930.44      94 2928.72
   105.1 2927.58   135.8 2926.42   166.2    2924   179.2 2924.17     208 2921.44
   220.7 2920.76   238.5 2921.28   271.4  2921.1   295.22920.059   299.9 2919.56
   316.3 2920.04   334.7 2920.86   344.1 2919.55   355.2 2920.66   359.3 2921.63
   371.9 2929.17   375.1 2929.71   384.8 2929.72   405.2 2930.87   415.4 2930.31
   427.4 2930.61   444.1 2932.38   449.8 2935.76   455.7 2938.33   468.5 2941.74
#Mann= 5 ,-1,0
       0      .1       0     210     .08       0   295.2    .045       0
   316.3     .08       0     400     .06       0
Bank Sta=295.2,316.3
XS Rating Curve= 0 ,0
Exp/Cntr(USF)=0,0
Exp/Cntr=0.3,0.1

Type RM Length L Ch R = 1 ,4694    ,276.3,278.9,278.2
XS GIS Cut Line= 2
2356495.04125679670858.0424125442356249.82692236670433.176740086
#Sta/Elev= 30
       0 2948.53    21.7 2940.42    33.3 2937.41    42.6 2934.29      61 2930.26
    70.1 2929.01      98 2926.91   109.8 2927.03   125.7 2925.44   166.7 2923.27
   176.5 2922.13     195 2921.73   208.8 2919.75   222.7 2918.68   241.2 2918.11
   273.5 2919.63     292 2916.58   313.1 2915.78   324.8 2915.01  334.912915.774
   342.8 2916.57     352 2915.63   365.9 2915.63   371.7 2916.34   375.1 2917.05
   397.8 2925.81   407.4 2927.94   430.5 2931.03   453.6 2933.14   490.6 2940.73
#Mann= 5 ,-1,0
       0      .1       0     210     .08       0   313.1    .045       0
  334.91     .06       0     440     .12       0
Bank Sta=313.1,334.91
XS Rating Curve= 0 ,0
Exp/Cntr(USF)=0,0
Exp/Cntr=0.3,0.1

Type RM Length L Ch R = 1 ,4415    ,265.8,269.2,265.6
XS GIS Cut Line= 2
2356716.32249432670727.8068549182356518.86301265670351.172998334
#Sta/Elev= 30
       0 2950.93       3 2949.24      12    2947      21 2943.45    26.2 2942.09
    34.8 2938.16    49.5 2934.63    62.8 2929.41    70.2 2927.24    77.8 2925.68
    93.3 2923.73   108.7 2922.64   172.6 2920.54   179.1 2919.51   188.1 2919.18
   219.8  2915.4   227.2 2913.75   233.3  2913.1   253.9 2912.71   269.4 2913.98
   278.5 2912.55   287.5 2913.29   296.5    2912   303.52913.292   313.2 2914.04
   322.1 2915.41   339.8 2919.84   351.7 2920.89   377.8 2925.53   425.3 2936.45
#Mann= 5 ,-1,0
       0      .1       0     280     .06       0   287.5    .045       0
   303.5     .06       0     390      .1       0
Bank Sta=287.5,303.5
XS Rating Curve= 0 ,0
Exp/Cntr(USF)=0,0
Exp/Cntr=0.3,0.1

Type RM Length L Ch R = 1 ,4146    ,242.7,248.4,238.5
XS GIS Cut Line= 2
2356863.20263386670615.7358536482356701.61469122670284.370711486
#Sta/Elev= 30
       0 2942.09    25.1  2932.1    42.9 2926.98      55 2922.32    65.1 2919.68
      76 2918.18    91.8 2918.19   114.1 2916.26   117.9 2914.93   123.8 2911.73
   127.5 2910.54   132.8  2910.2   147.8 2910.62   158.6 2909.74   163.1 2909.85
  166.962910.638     172 2911.25   180.9 2910.88   198.6 2911.59   234.3    2911
   243.5 2911.97   252.1 2912.12   256.5    2912   267.4 2910.41   271.6 2910.45
   280.7 2912.86   297.3 2920.04   305.5 2921.19   333.2 2928.83   368.7  2941.9
#Mann= 6 ,-1,0
       0      .1       0      60     .08       0   147.8    .045       0
  166.96     .08       0     260     .06       0  368.66      .1       0
Bank Sta=147.8,166.96
XS Rating Curve= 0 ,0
Exp/Cntr(USF)=0,0
Exp/Cntr=0.3,0.1

Type RM Length L Ch R = 1 ,3897    ,383.3,386.4,380.4
XS GIS Cut Line= 2
 2357038.1827871670533.9901307482356854.04013729670178.896502926
#Sta/Elev= 30
       0 2943.99     5.4 2941.75      14 2939.29    19.9  2936.2    28.8 2933.17
    39.1 2928.56      55 2924.34    68.5 2918.59    88.1 2916.35   129.7 2914.28
   136.1 2913.16   145.1 2908.82  166.662908.156   177.2  2907.4   186.1 2908.13
   197.9 2909.71   203.7 2909.78   244.2 2906.79   253.2 2908.59   260.2 2908.81
   275.8 2910.69   286.9 2916.79   320.8 2925.54   351.9 2936.77   361.4 2939.54
   370.4 2944.15   379.4  2945.4   383.9 2947.52   388.4  2950.4     400 2955.12
#Mann= 4 ,-1,0
       0      .1       0  166.66    .045       0   186.1     .06       0
     280      .1       0
Bank Sta=166.66,186.1
XS Rating Curve= 0 ,0
Exp/Cntr(USF)=0,0
Exp/Cntr=0.3,0.1

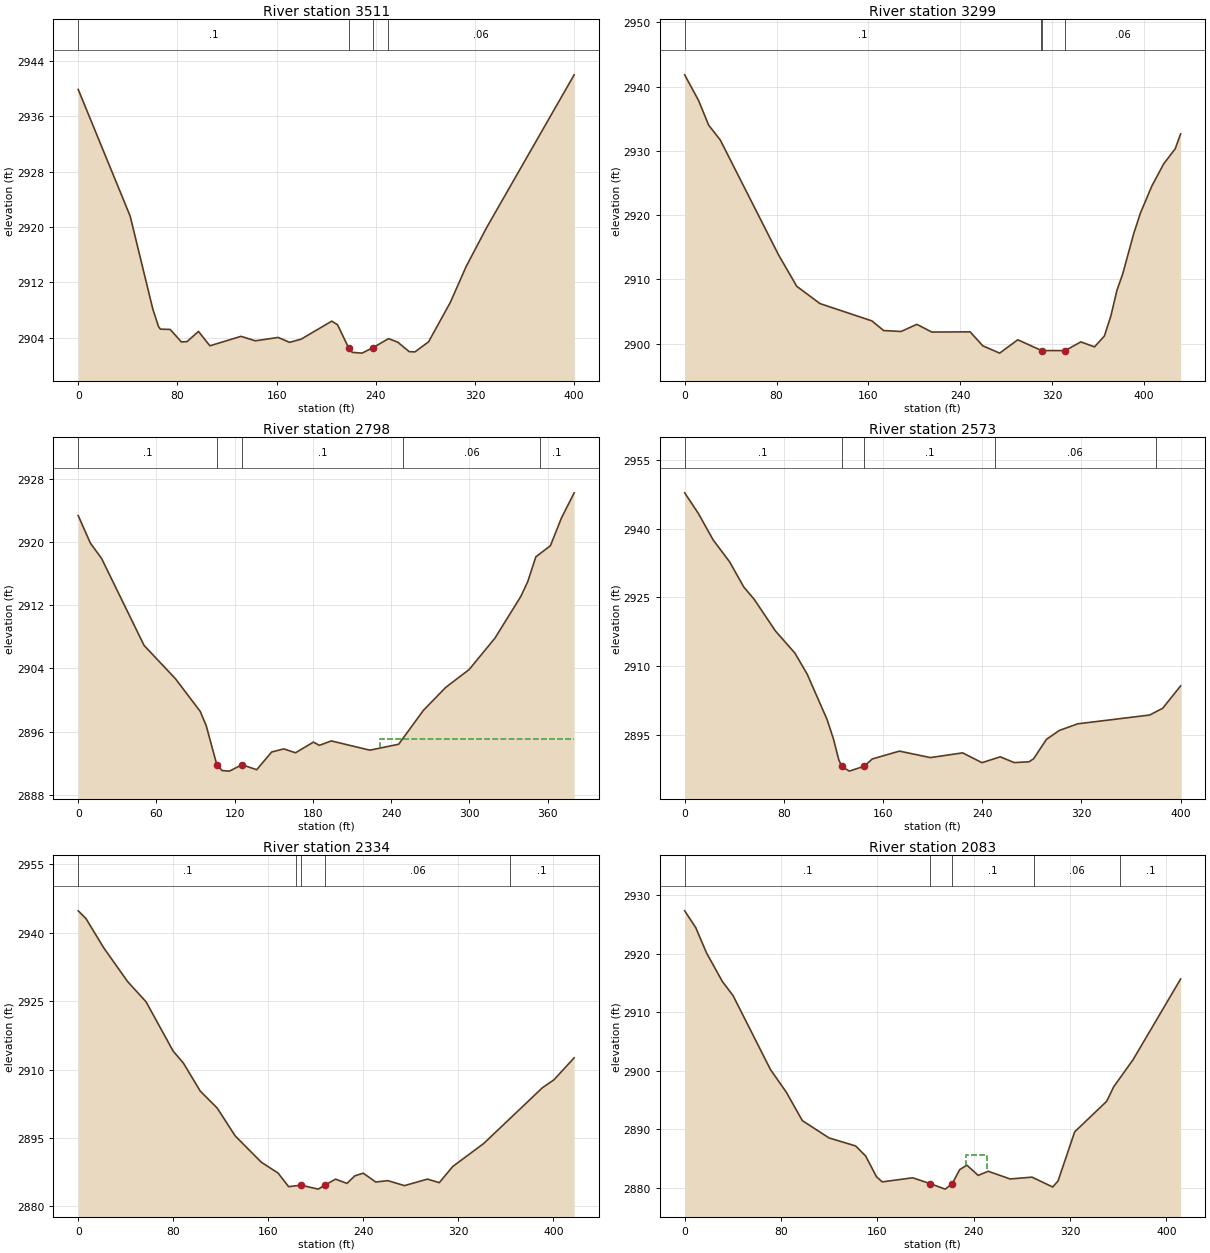
Type RM Length L Ch R = 1 ,3511    ,213.1,212.1,210
XS GIS Cut Line= 2
2357348.76650144670405.6291275062357152.03702641670057.351201626
#Sta/Elev= 30
       0 2939.92    41.9 2921.59    60.2 2908.12    64.8  2905.6    66.3 2905.23
    74.2 2905.19    83.2 2903.38    87.8 2903.43      97  2904.9   106.2 2902.82
   131.3 2904.19   142.9 2903.54   161.3 2904.03   170.5 2903.32   179.8 2903.78
   204.5 2906.39   209.2 2905.86     218 2902.56     221 2901.87   228.9 2901.76
  237.882902.565   250.3 2903.86   257.8 2903.34     267 2901.97   271.6 2901.94
   282.6  2903.4   300.2 2909.13   312.9  2914.3   329.6 2919.99     400 2942.03
#Mann= 4 ,-1,0
       0      .1       0     218    .045       0  237.88      .1       0
     250     .06       0
Bank Sta=218,237.88
XS Rating Curve= 0 ,0
Exp/Cntr(USF)=0,0
Exp/Cntr=0.3,0.1

Type RM Length L Ch R = 1 ,3299    ,499.4,500.5,503.4
XS GIS Cut Line= 2
2357600.78021069670333.6300001592357334.59465875669993.506467346
#Sta/Elev= 30
       0 2941.82    12.1 2937.83    20.9 2933.99      31 2931.68    81.8 2913.79
    97.6 2908.92   117.8 2906.23   163.1 2903.53   173.3 2902.03   188.5 2901.89
   202.2    2903   215.2  2901.8   248.6 2901.83   259.6 2899.66   274.3 2898.52
   290.1  2900.6  310.83 2898.92   331.3 2898.91     345 2900.27   356.9 2899.49
   365.5 2901.18   371.2 2904.33   376.4 2908.27   381.5 2910.86   391.1 2917.14
   396.9 2920.32   406.9 2924.54   417.1 2927.95   427.2 2930.32   431.9 2932.63
#Mann= 4 ,-1,0
       0      .1       0     310     .06       0  310.83    .045       0
   331.3     .06       0
Bank Sta=310.83,331.3
XS Rating Curve= 0 ,0
Exp/Cntr(USF)=0,0
Exp/Cntr=0.3,0.1

Type RM Length L Ch R = 1 ,2798    ,226.9,225,223.5
XS GIS Cut Line= 4
2357931.34564784670099.1692813452357887.61342723670059.343514736
2357793.54813917669888.7624326432357703.16922902669800.256450548
#Sta/Elev= 30
       0 2923.32     9.3 2919.85    17.9 2917.91    50.5 2906.91    74.6 2902.69
    93.6 2898.56    98.2 2896.75  106.34  2891.8   110.4 2891.08     116 2891.01
   125.6 2891.82   136.9 2891.19   148.4 2893.43   157.7 2893.82   166.7 2893.33
   180.4 2894.68     185 2894.27   194.1 2894.83   223.7 2893.66   245.8 2894.41
   264.8  2898.7   281.9  2901.6   299.9 2903.86   319.7 2907.84   339.5  2913.1
   344.8 2914.97     351  2918.1   362.2 2919.52   370.6    2923   380.4  2926.2
#Mann= 5 ,-1,0
       0      .1       0  106.34    .045       0   125.6      .1       0
  249.15     .06       0  353.95      .1       0
#XS Ineff= 2 , 0
                          231.15         2895.07
Permanent Ineff=
       F       F
Bank Sta=106.34,125.6
XS Rating Curve= 0 ,0
Exp/Cntr(USF)=0,0
Exp/Cntr=0.3,0.1

Type RM Length L Ch R = 1 ,2573    ,240.7,238.9,235.9
XS GIS Cut Line= 2
2358130.90159285669985.5320446032357875.11588057669678.003721689
#Sta/Elev= 30
       0  2947.8    10.9 2943.37      23 2937.52    36.3 2932.74    47.6  2927.3
    56.2 2924.54    73.2 2917.69    88.9 2912.87    98.8 2908.29   114.9 2898.36
   120.1 2894.06   124.3  2889.6  126.72 2888.17   132.8 2887.14  144.832888.216
   151.3 2889.79   173.2  2891.5   198.2 2890.09   224.2 2891.12   239.8 2888.98
   254.5 2890.26   265.8    2889   277.7 2889.17   281.4 2889.83   291.8 2894.07
   302.2 2896.01     317 2897.45   375.1 2899.37   385.5 2900.84     400 2905.71
#Mann= 5 ,-1,0
       0      .1       0  126.72    .045       0  144.83      .1       0
     250     .06       0     380      .1       0
Bank Sta=126.72,144.83
XS Rating Curve= 0 ,0
Exp/Cntr(USF)=0,0
Exp/Cntr=0.3,0.1

Type RM Length L Ch R = 1 ,2334    ,242.4,251.7,253.8
XS GIS Cut Line= 3
2358306.98377475669838.318822591 2358207.9266306669708.062577919
 2357998.1126796 669565.32669304
#Sta/Elev= 30
       0 2944.83     6.5 2943.15    21.5 2936.71    41.6 2929.31    57.1 2924.88
    79.9 2914.07    88.5 2911.45   102.7  2905.3     117 2901.57   132.1 2895.47
   154.1 2889.69   168.2 2887.32   177.1 2884.33   187.5 2884.66     202 2883.79
  207.772884.692   216.6 2885.98   226.2 2885.05   232.8  2886.7   239.9 2887.29
   250.4 2885.35   260.6 2885.65   274.6 2884.56     294 2885.99   303.9 2885.21
   315.3 2888.77   341.2 2893.78   390.7 2906.03   400.4 2907.77   417.4 2912.59
#Mann= 5 ,-1,0
       0      .1       0  183.64     .06       0   187.5    .045       0
  207.77     .06       0  363.64      .1       0
Bank Sta=187.5,207.77
XS Rating Curve= 0 ,0
Exp/Cntr(USF)=0,0
Exp/Cntr=0.3,0.1

Type RM Length L Ch R = 1 ,2083    ,338.1,340.6,338.4
XS GIS Cut Line= 3
2358435.99231738669721.5174725612358302.68636064669439.742796214
2358252.30617425669353.142577222
#Sta/Elev= 30
       0 2927.35     9.2 2924.48    18.1 2920.17    31.3 2915.26    40.2 2912.84
    71.2 2900.21    84.5 2896.29    97.7 2891.46   119.9 2888.49     142 2887.12
   150.3  2885.4   159.3 2881.85   164.1 2880.97   189.4 2881.67   203.9 2880.67
   216.4 2879.73  222.242880.672   228.4 2883.06   234.4 2883.83   243.8 2882.08
   252.1 2882.79   270.3 2881.47   288.5 2881.78   305.7 2880.09   310.1 2881.13
   323.9 2889.53   350.5 2894.76   356.3 2897.23   372.4 2901.88   411.9 2915.68
#Mann= 5 ,-1,0
       0      .1       0   203.9    .045       0  222.24      .1       0
     290     .06       0  361.72      .1       0
#XS Ineff= 1 ,-1
  233.47  250.71 2885.53
Permanent Ineff=
       F
Bank Sta=203.9,222.24
XS Rating Curve= 0 ,0
Exp/Cntr(USF)=0,0
Exp/Cntr=0.3,0.1

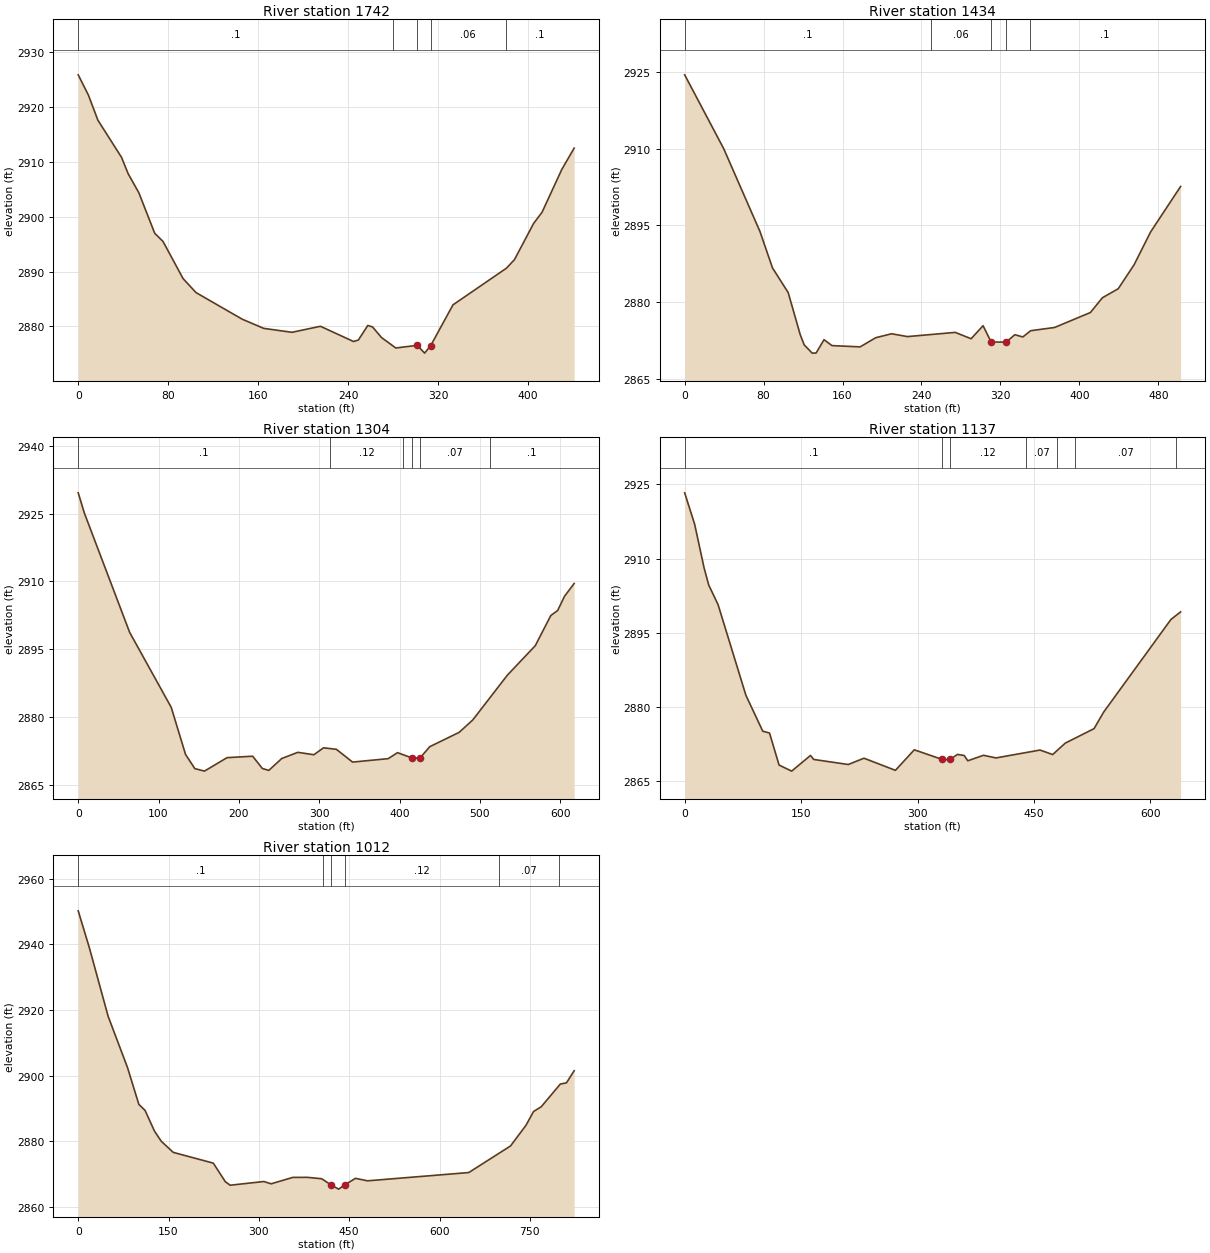
Type RM Length L Ch R = 1 ,1742    ,306.1,308,308.7
XS GIS Cut Line= 2
 2358659.6077603669661.7888196212358522.54892057669242.863993208
#Sta/Elev= 30
       0 2925.92     9.1  2922.2    17.5 2917.64    38.5 2910.86    44.4 2907.87
    53.9 2904.39      68    2897    75.4  2895.5    93.2 2888.73   104.7 2886.17
   145.9  2881.3   164.9 2879.64     190 2878.92   215.3 2880.02   244.7 2877.24
     249 2877.51   257.4 2880.17   261.6  2879.9   269.6 2877.96   282.3 2876.06
   301.3 2876.54   307.9 2875.12  313.352876.505   333.1 2883.93   380.6 2890.62
   387.8  2892.2   404.7 2898.77   412.3 2900.85   429.9 2908.68   440.8 2912.54
#Mann= 5 ,-1,0
       0      .1       0     280     .06       0   301.3    .045       0
  313.35     .06       0     380      .1       0
Bank Sta=301.3,313.35
XS Rating Curve= 0 ,0
Exp/Cntr(USF)=0,0
Exp/Cntr=0.3,0.1

Type RM Length L Ch R = 1 ,1434    ,130.8,129.9,130.2
XS GIS Cut Line= 3
2358870.12753914669648.004309418 2358891.9669095669540.367412623
2358845.16825872669150.378656122
#Sta/Elev= 30
       0 2924.41    39.6 2909.97    76.3 2893.81      89  2886.7   104.9 2881.89
   117.1 2873.67   121.1 2871.68   129.2 2870.06   133.2 2870.08   141.2 2872.68
   149.3 2871.53   177.8 2871.28   193.6 2873.07   209.7 2873.84   225.8 2873.29
   274.2 2874.11   290.3 2872.87   302.4 2875.42   310.6 2872.22  325.862872.218
   334.6 2873.66   342.7 2873.22   350.7 2874.44   374.9 2875.07   411.2 2877.99
   423.3 2880.87   439.4 2882.64   455.5 2887.33   472.2 2893.73   502.6 2902.61
#Mann= 5 ,-1,0
       0      .1       0  249.83     .06       0   310.6    .045       0
  325.86     .06       0  349.83      .1       0
Bank Sta=310.6,325.86
XS Rating Curve= 0 ,0
Exp/Cntr(USF)=0,0
Exp/Cntr=0.3,0.1

Type RM Length L Ch R = 1 ,1304    ,167.1,167.3,170.6
XS GIS Cut Line= 4
 2358949.8489224669696.4438469382359000.20021514669572.615003674
2358984.04109254  669244.05723332358934.08753042669097.798322936
#Sta/Elev= 30
       0  2929.6     7.8 2925.05      64 2898.73   115.8 2882.11   133.6 2871.69
   145.1 2868.57   157.1 2868.01   185.2 2870.99   217.1 2871.31   229.2 2868.59
   237.2 2868.17   253.3  2870.8   273.3 2872.17   293.3 2871.64   305.3 2873.17
   321.3 2872.84   341.4 2870.01   385.8 2870.77   397.4  2872.1   415.3 2870.93
   425.5 2870.94   437.5 2873.42   474.1 2876.59     491 2879.33   534.1 2889.25
   568.8 2895.77   588.2 2902.45   596.7 2903.56   605.2  2906.7   617.2 2909.53
#Mann= 6 ,-1,0
       0      .1       0  313.67     .12       0  403.67     .07       0
   415.3    .045       0   425.5     .07       0  512.63      .1       0
Bank Sta=415.3,425.5
XS Rating Curve= 0 ,0
Exp/Cntr(USF)=0,0
Exp/Cntr=0.3,0.1

Type RM Length L Ch R = 1 ,1137    ,128.5,125.1,116.6
XS GIS Cut Line= 4
2358971.52461583669702.6027353282359044.84250205669620.705096463
2359105.68074807669242.4160026562359069.02180496669101.240072802
#Sta/Elev= 30
       0  2923.3    12.8 2916.98      25 2908.13      31 2904.66      43 2900.71
    78.9 2882.37   100.6 2875.12   109.3 2874.75   121.6 2868.28   137.8 2867.05
   162.1 2870.22   166.2 2869.41   210.7 2868.39     231 2869.66   271.5 2867.21
   295.8 2871.36  331.782869.411   341.9 2869.41   351.5 2870.43   360.2  2870.2
   364.7 2869.14   384.9 2870.25   401.1 2869.72   457.8 2871.31   474.1  2870.4
   490.3 2872.71   527.4 2875.64   539.8 2878.99   626.4  2897.7   638.9 2899.24
#Mann= 7 ,-1,0
       0      .1       0  331.78    .045       0   341.9     .12       0
  439.92     .07       0  479.92     .12       0  503.07     .07       0
  633.07      .1       0
Bank Sta=331.78,341.9
XS Rating Curve= 0 ,0
Exp/Cntr(USF)=0,0
Exp/Cntr=0.3,0.1

Type RM Length L Ch R = 1 ,1012    ,242.9,252.7,247.5
XS GIS Cut Line= 4
2359001.52831515 669816.312794872359170.30982428669681.287587563
2359155.63317131669218.9730190662359111.60321241669081.012481166
#Sta/Elev= 30
       0  2950.2    18.8 2938.77    49.6 2918.11    81.9 2902.42   100.7 2891.22
     111  2889.4   126.5 2883.13   137.9 2879.99   157.8  2876.6   224.3 2873.32
   244.3 2867.66   252.3 2866.59   308.3 2867.72   320.3 2867.02   356.3 2868.97
   380.3 2868.99   404.2 2868.57   420.4 2866.62   432.4  2865.4  442.372866.643
   460.4 2868.69   480.4 2867.93   648.5 2870.45   717.9 2878.56   743.6 2884.87
   756.1 2889.05   768.8 2890.49   800.6 2897.42   810.7 2897.78   823.5 2901.47
#Mann= 6 ,-1,0
       0      .1       0  406.15     .12       0   420.4    .045       0
  442.37     .12       0  698.69     .07       0  798.69      .1       0
Bank Sta=420.4,442.37
XS Rating Curve= 0 ,0
Exp/Cntr(USF)=0,0
Exp/Cntr=0.3,0.1