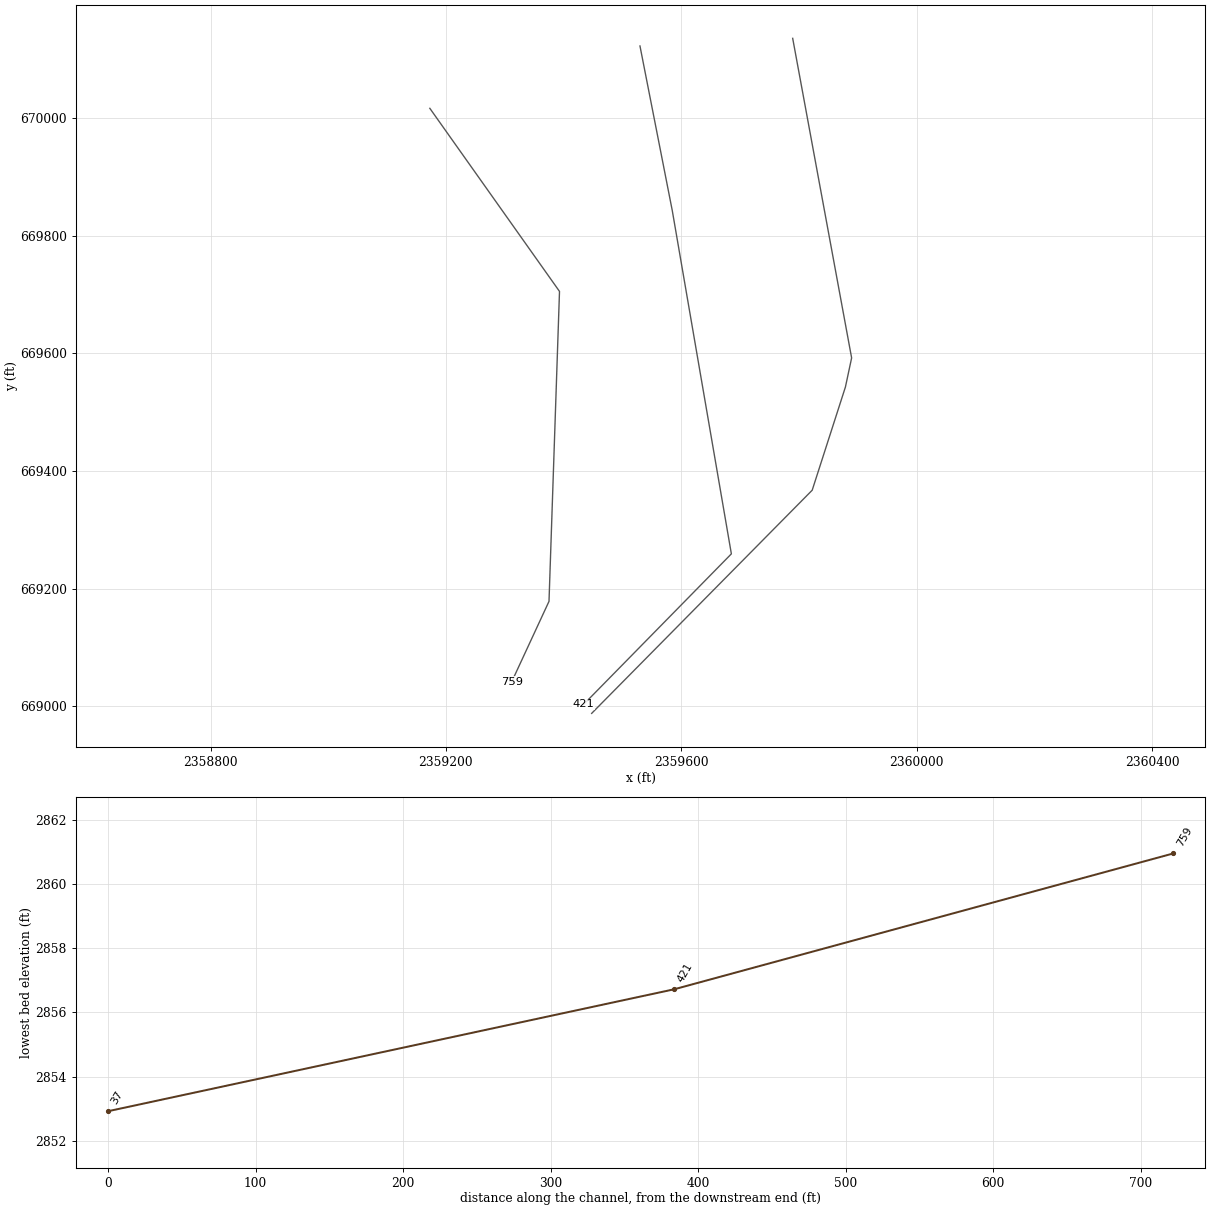
HEC-RAS study BEAVERDMRN.prj: BEAVERDMRN

--- BEAVERDMRN.g01 (geometry) --- (continued)

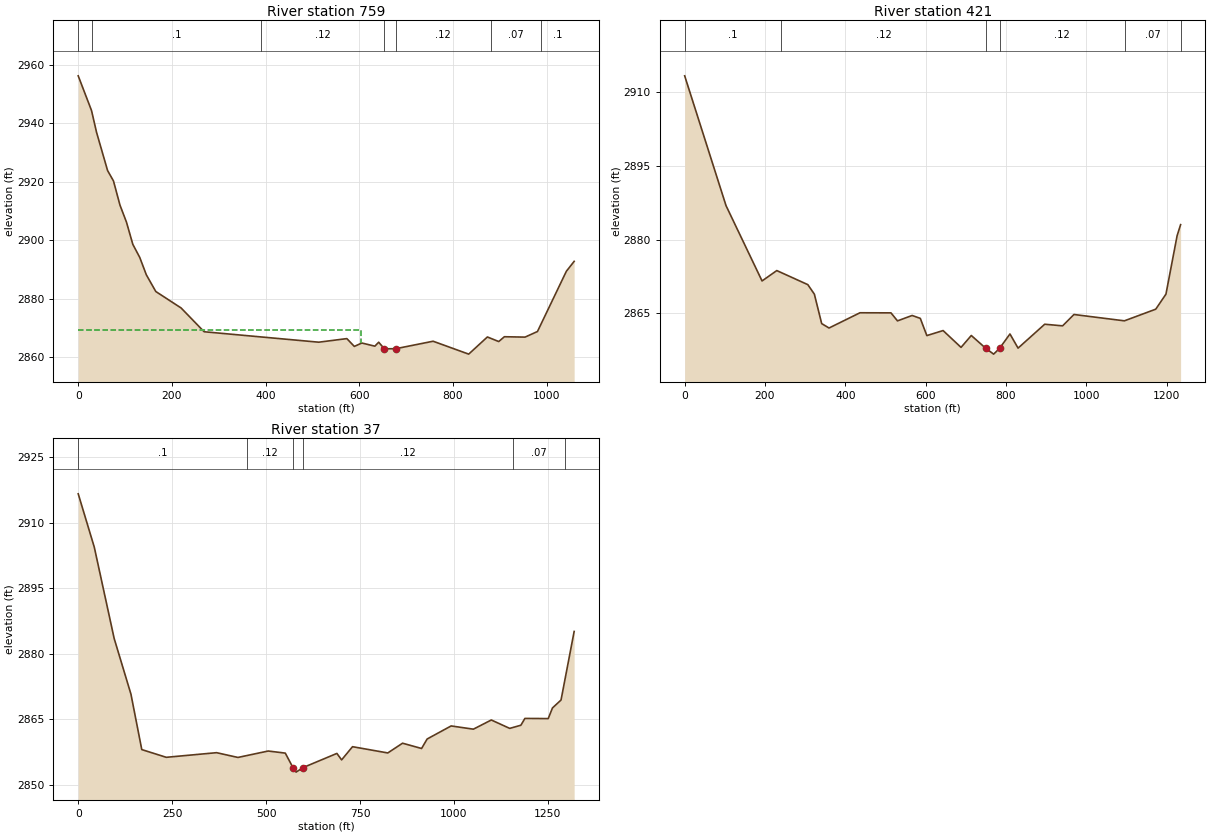
Type RM Length L Ch R = 1 ,759     ,330.7,338.3,343
XS GIS Cut Line= 4
2359172.65528393670016.3422014092359392.98267253669705.286075844
2359375.15053917669178.643737391 2359311.8930082669042.164745413
#Sta/Elev= 30
       0 2956.33    28.4 2944.44    39.2 2936.93    62.7 2923.87    75.3 2920.29
    89.1 2912.04     103 2906.19   116.6 2898.57   131.3 2894.11   145.4 2888.14
   165.6 2882.41   219.6 2876.77   268.8 2868.62   513.4 2865.04   573.4 2866.27
   589.4 2863.59   605.4 2864.76   633.2 2863.68   641.4 2865.03   653.4 2862.78
   677.5  2862.8   757.5 2865.37   833.5 2860.95   873.4 2866.83   897.6 2865.26
   909.7 2866.91   953.8 2866.78   980.3  2868.7    1042 2889.35  1058.6 2892.74
#Mann= 7 ,-1,0
       0     .07       0      30      .1       0  391.18     .12       0
   653.4    .045       0   677.5     .12       0  881.18     .07       0
  988.13      .1       0
#XS Ineff= 2 , 0
          604.21 2869.32
Permanent Ineff=
       F       F
Bank Sta=653.4,677.5
XS Rating Curve= 0 ,0
Exp/Cntr(USF)=0,0
Exp/Cntr=0.3,0.1

Type RM Length L Ch R = 1 ,421     ,369.4,384,354.8
XS GIS Cut Line= 4
2359529.70111977670122.285389306 2359584.5702897669842.738539764
2359685.00922454669259.322227996 2359434.0753033669003.644248145
#Sta/Elev= 30
       0 2913.31     103 2886.91   192.7  2871.6   229.4 2873.71   306.7 2870.85
     323 2868.91   341.2 2862.93   359.5 2862.03   436.6 2865.13   513.8 2865.11
     530 2863.48   566.5 2864.58   586.8 2863.99   603.1 2860.49   643.6 2861.51
   688.3 2858.09   713.8 2860.51   749.9  2857.9   769.5 2856.72  784.192857.891
   810.1 2860.82   830.3 2857.94   896.7  2862.8   941.2 2862.47   969.5 2864.78
  1095.1 2863.49  1173.2 2865.86  1198.6 2868.92  1226.4  2880.8  1235.1 2883.05
#Mann= 6 ,-1,0
       0      .1       0     240     .12       0   749.9    .045       0
  784.19     .12       0 1096.88     .07       0 1235.12      .1       0
Bank Sta=749.9,784.19
XS Rating Curve= 0 ,0
Exp/Cntr(USF)=0,0
Exp/Cntr=0.3,0.1

Type RM Length L Ch R = 1 ,37      ,,,
XS GIS Cut Line= 5
2359789.19396963670135.2693552942359889.33797699669592.270106206
2359878.80494095669542.8620346262359822.35924394669367.499201273
 2359447.6246985668988.287009124
#Sta/Elev= 30
       0 2916.61    42.8  2904.4    95.7 2883.51   140.4 2870.75   169.2 2858.08
   234.4 2856.31   368.2 2857.37   425.1 2856.28   505.7 2857.75   551.2 2857.27
  571.532853.959   579.9 2852.92   598.32853.957   688.5  2857.2   701.1 2855.72
   730.1 2858.74     824 2857.31   863.3 2859.54   913.9 2858.33   928.7  2860.5
   992.6 2863.49  1051.8 2862.75  1099.5 2864.85  1148.5 2862.93  1178.2 2863.65
  1188.9 2865.21    1251 2865.17  1262.3 2867.61  1285.1 2869.42    1320 2885.11
#Mann= 6 ,-1,0
       0      .1       0     450     .12       0  571.53    .045       0
   598.3     .12       0  1156.9     .07       0  1296.9      .1       0
Bank Sta=571.53,598.3
XS Rating Curve= 0 ,0
Exp/Cntr(USF)=0,0
Exp/Cntr=0.3,0.1
LCMann Table=0

Chan Stop Cuts=-1
Use User Specified Reach Order=0
Composite Channel Slope=5